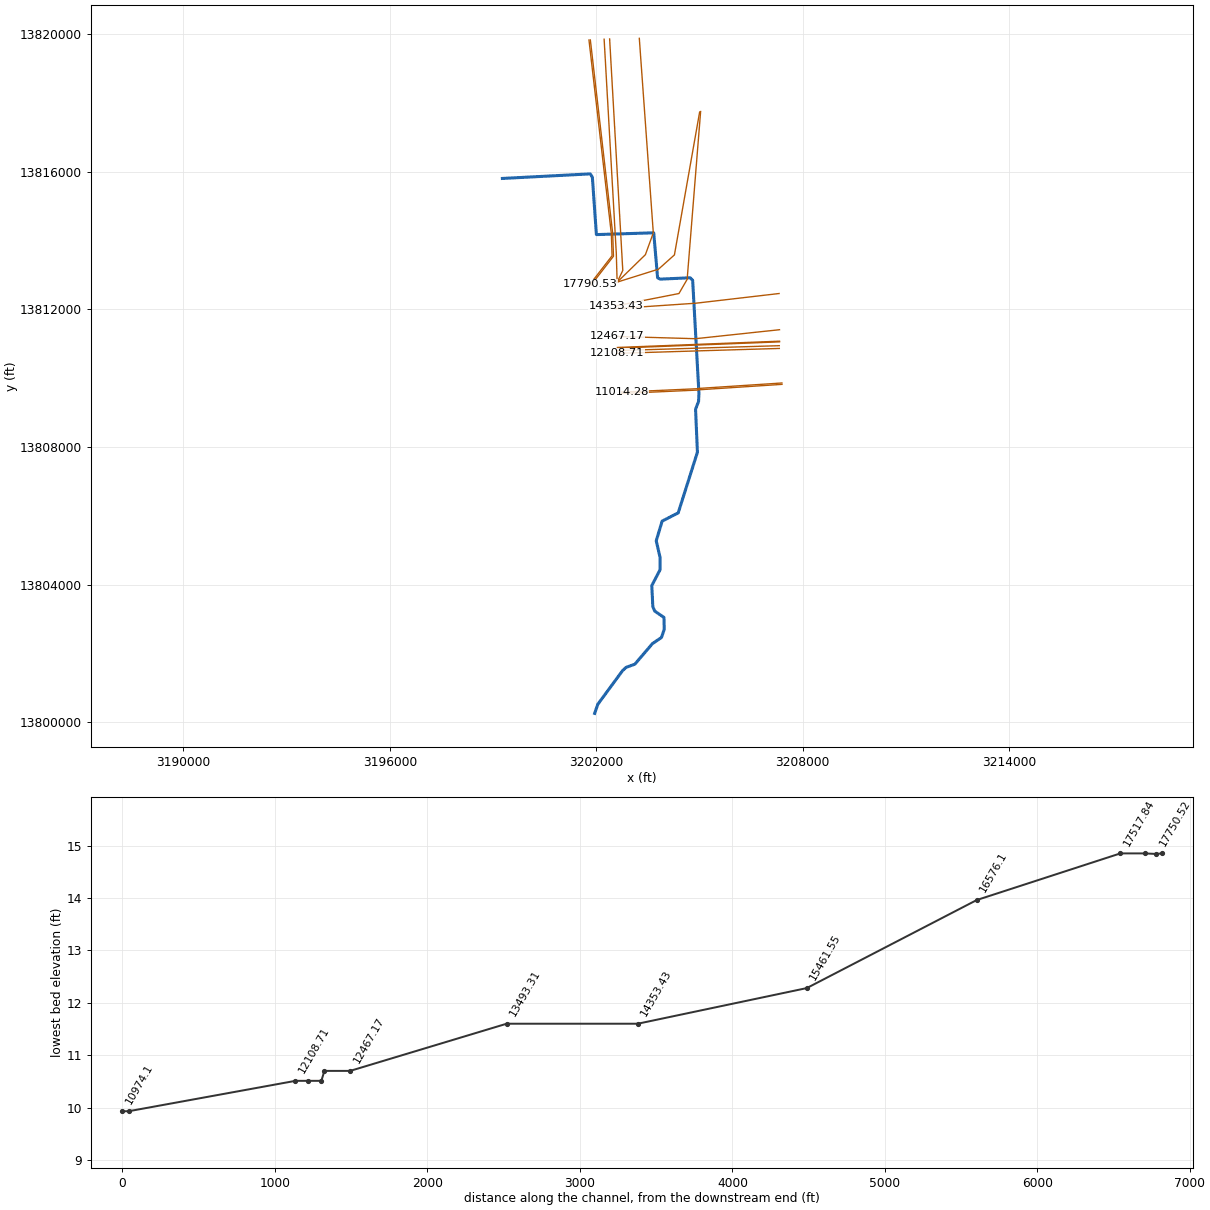
--- B112-00-00.prj (project) ---

Proj Title=B112-00-00
Current Plan=p05
Default Exp/Contr=.3,.1
English Units
Geom File=g02
Flow File=f06
Flow File=f01
Plan File=p03
Plan File=p05
Y Axis Title=Elevation
X Axis Title(PF)=Main Channel Distance
X Axis Title(XS)=Station
BEGIN DESCRIPTION:
Armand Bayou
Willow Springs Bayou
HCFCD Unit B112-00-00
Flood Hazard Model
10, 2, 1, 0.2% Event
Filename B112-00-00.prj
Prepared by: Christopher Moss Date: 6/15/2004
Reviewd by:		Date:
Status FINAL
END DESCRIPTION:
DSS Export Rating Curves= 0
DSS Export Rating Curve Sorted= 0
DSS Export Volume Flow Curves= 0
DXF OffsetX= 0
DXF OffsetY= 0
DXF ScaleX= 1
DXF ScaleY= 10

--- B112-00-00.p05 (plan) ---

Plan Title=Floodway
Version=Version 3.0.1  Mar 2001
Short Identifier=Floodway0607
Geom File=g02
Flow File=f01
Subcritical Flow
K Sum by GR= 0
Std Step Tol= 0.01
Critical Tol= 0.01
Num of Std Step Trials= 20
Max Error Tol= 0.3
Flow Tol Ratio= 0.001
Split Flow NTrial= 30
Split Flow Tol= 0.02
Split Flow Ratio= 0.02
Log Output Level= 0
Friction Slope Method= 0
Unsteady Friction Slope Method= 2
Secant Critical Depth
Global Vel Dist= 0 , 0 , 0
Global Log Level= 0
CheckData=True
Encroach Param=-1 ,0,0, 2
Encroach River=B112-00-00
Encroach Reach=MAIN
Encroach Node=17790.53
       1 4966.84 5033.16
Encroach Node=17750.52
       1  4961.5  5038.5
Encroach Node=17717.18
       4    4956    5033
Encroach Node=17677.84
       1    4956    5033
Encroach Node=17517.84
       1 4935.66 5062.86
Encroach Node=16576.1
       1 5576.06 5672.56
Encroach Node=15461.55
       1 4944.95 5060.65
Encroach Node=14353.43
       1    7278    7350
Encroach Node=13493.31
       1 4966.79 5033.21
Encroach Node=12467.17
       1 4967.09 5032.91
Encroach Node=12298.35
       1 4967.09 5032.91
Encroach Node=12278.35
       1  4967.2  5032.8
Encroach Node=12233.54
       1  4967.2  5032.8
Encroach Node=12188.72
       1  4967.2  5032.8
Encroach Node=12108.71
       1  4967.2  5032.8
Encroach Node=11014.28
       1  4966.9  5033.1
Encroach Node=10974.1
       1 4960.03 5039.97
Encroach Node=10883.27
       1 4960.03 5039.97
Encroach Node=10792.43
       1 4960.03 5039.97
Encroach Node=10610.83
       1 4960.03 5039.97
Encroach Node=10067.4
       1 4959.48 5040.52
Encroach Node=10027.4
       1 4958.07 5043.31
Encroach Node=9938
       1 4958.07 5043.31
Encroach Node=9849.865
       1 4958.07 5043.31
Encroach Node=9638.195
       1 4911.36 5040.52
Encroach Node=8821.352
       1 4897.08 5062.59
Encroach Node=8577.462
       1  4923.2 5108.87
Encroach Node=7798.68
       1 4910.38 5057.36
Encroach Node=7597.597
       1  4931.6  5068.4
Encroach Node=6639.987
       1 4929.56 5070.44
Encroach Node=5658.061
       1 4893.47 5142.66
Encroach Node=5616.164
       1 4912.15 5057.85
Encroach Node=5475
       1 4912.15 5057.85
Encroach Node=5334.138
       1 4927.15 5072.85
Encroach Node=5148.595
       1 4927.15 5072.85
Encroach Node=4410.717
       1 4925.73 5074.27
Encroach Node=3531.853
       1 4925.44 5074.56
Encroach Node=2454.362
       1  4923.9  5076.1
Encroach Node=1503.073
       1 4917.72 5072.35
Encroach Node=1462.72
       1 4887.94 5092.14
Encroach Node=1354.8
       1 4887.94 5092.14
Encroach Node=1246.85
       1 4919.99 5124.19
Encroach Node=1141.6
       1 4919.99 5124.19
Encroach Node=1036.333
       1 4908.57 5112.77
Encroach Node=854.41
       1    4921 5087.28
Encroach Reach=B112-00-00_0009
Encroach Node=17790.53
       1 4966.84 5033.16
Encroach Node=17750.52
       1  4961.5  5038.5
Encroach Node=17717.18
       4    4956    5033
Encroach Node=17677.84
       1    4956    5033
Encroach Node=17517.84
       1 4935.66 5062.86
Encroach Node=16576.1
       1 5576.06 5672.56
Encroach Node=15461.55
       1 4944.95 5060.65
Encroach Node=14353.43
       1    7278    7350
Encroach Node=13493.31
       1 4966.79 5033.21
Encroach Node=12467.17
       1 4967.09 5032.91
Encroach Node=12298.35
       1 4967.09 5032.91
Encroach Node=12278.35
       1  4967.2  5032.8
Encroach Node=12233.54
       1  4967.2  5032.8
Encroach Node=12188.72
       1  4967.2  5032.8
Encroach Node=12108.71
       1  4967.2  5032.8
Encroach Node=11014.28
       1  4966.9  5033.1
Encroach Node=10974.1
       1 4960.03 5039.97
Encroach Node=10883.27
       1 4960.03 5039.97
Encroach Node=10792.43
       1 4960.03 5039.97
Encroach Node=10610.83
       1 4960.03 5039.97
Encroach Node=10067.4
       1 4959.48 5040.52
Encroach Node=10027.4
       1 4958.07 5043.31
Encroach Node=9938
       1 4958.07 5043.31
Encroach Node=9849.865
       1 4958.07 5043.31
Encroach Node=9638.195
       1 4911.36 5040.52
Encroach Node=8821.352
       1 4897.08 5062.59
Encroach Node=8577.462
       1  4923.2 5108.87
Encroach Node=7798.68
       1 4910.38 5057.36
Encroach Node=7597.597
       1  4931.6  5068.4
Encroach Node=6639.987
       1 4929.56 5070.44
Encroach Node=5658.061
       1 4893.47 5142.66
Encroach Node=5616.164
       1 4912.15 5057.85
Encroach Node=5475
       1 4912.15 5057.85
Encroach Node=5334.138
       1 4927.15 5072.85
Encroach Node=5148.595
       1 4927.15 5072.85
Encroach Node=4410.717
       1 4925.73 5074.27
Encroach Node=3531.853
       1 4925.44 5074.56
Encroach Node=2454.362
       1  4923.9  5076.1
Encroach Node=1503.073
       1 4917.72 5072.35
Encroach Node=1462.72
       1 4887.94 5092.14
Encroach Node=1354.8
       1 4887.94 5092.14
Encroach Node=1246.85
       1 4919.99 5124.19
Encroach Node=1141.6
       1 4919.99 5124.19
Encroach Node=1036.333
       1 4908.57 5112.77
Encroach Node=854.41
       1    4921 5087.28
Computation Interval=1HOUR
Output Interval=1HOUR
Run HTab= 0
Run UNet= 0
Run PostProcess= 0
UNET Theta= 1
UNET ZTol= 0.02
UNET ZSATol= 0.1
UNET MxIter= 20
UNET MaxInSteps= 20
UNET DtIC= 0
UNET DtMin= 0
UNET MaxCRTS= 20
UNET WFStab= 2
UNET SFStab= 1
UNET WFX= 1
UNET SFX= 1
UNET Convert EG Bridges=-1
UNET Use Existing IB Tables=-1
Instantaneous Interval=1HOUR
Write IC File= 0
IC Time=0
Write Velocity= 0
Write Detailed= 0

--- B112-00-00.p03 (plan) ---

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Plan Title=FEMA Effective June 2007
Short Identifier=FEMAeff0607
Geom File=g02
Flow File=f06
Encroach Param=-1 ,0,0, 0
BEGIN DESCRIPTION:
Baker Revised
END DESCRIPTION:

--- B112-00-00.f01 (steady flow) ---

Flow Title=Floodway
Version=Version 3.0.1  Mar 2001
Number of Profiles= 2
Profile Names=1PCT_100yr, 1PCTFloodway_100yrFW
River Rch & RM=B112-00-00,B112-00-00_0009            ,17790.53
    1120    1120
River Rch & RM=B112-00-00,B112-00-00_0009            ,17677.84
    1197    1197
River Rch & RM=B112-00-00,B112-00-00_0009            ,17517.84
    1766    1766
River Rch & RM=B112-00-00,B112-00-00_0009            ,16576.1
    2053    2053
River Rch & RM=B112-00-00,B112-00-00_0009            ,15461.55
    2385    2385
River Rch & RM=B112-00-00,B112-00-00_0009            ,14353.43
    2460    2460
River Rch & RM=B112-00-00,B112-00-00_0009            ,13493.31
    2569    2569
River Rch & RM=B112-00-00,B112-00-00_0009            ,12298.35
    2690    2690
River Rch & RM=B112-00-00,B112-00-00_0009            ,11014.28
    2730    2730
River Rch & RM=B112-00-00,B112-00-00_0009            ,10610.83
    2827    2827
River Rch & RM=B112-00-00,B112-00-00_0009            ,9638.195
    3264    3264
River Rch & RM=B112-00-00,B112-00-00_0009            ,8821.352
    3429    3429
River Rch & RM=B112-00-00,B112-00-00_0009            ,7798.68
    3462    3462
River Rch & RM=B112-00-00,B112-00-00_0009            ,7597.597
    3625    3625
River Rch & RM=B112-00-00,B112-00-00_0009            ,6639.987
    3800    3800
River Rch & RM=B112-00-00,B112-00-00_0009            ,5658.061
    3895    3895
River Rch & RM=B112-00-00,B112-00-00_0009            ,5148.595
    4035    4035
River Rch & RM=B112-00-00,B112-00-00_0009            ,4410.717
    4209    4209
River Rch & RM=B112-00-00,B112-00-00_0009            ,3531.853
    4433    4433
River Rch & RM=B112-00-00,B112-00-00_0009            ,2454.362
    4650    4650
River Rch & RM=B112-00-00,B112-00-00_0009            ,1246.85
    4788    4788
Boundary for River Rch & Prof#=B112-00-00,B112-00-00_0009            , 1
Up Type= 0
Dn Type= 3
Dn Slope=.00232
DSS Import GetInterval= 0
DSS Import GetPeak= 0
DSS Import FillOption= 0

--- B112-00-00.f06 (steady flow) ---

Flow Title=FEMA Effective June 2007
Version=Version 3.0.1  Mar 2001
Number of Profiles= 4
Profile Names=10PCT_10yr, 2PCT_50yr, 1PCT_100yr, 0.2PCT_500yr
River Rch & RM=Willow_Springs,B112-00-00      ,17790.53
     664     964    1120    1569
River Rch & RM=Willow_Springs,B112-00-00      ,17677.84
     709    1030    1197    1676
River Rch & RM=Willow_Springs,B112-00-00      ,17517.84
    1046    1519    1766    2473
River Rch & RM=Willow_Springs,B112-00-00      ,16576.1
    1216    1766    2053    2875
River Rch & RM=Willow_Springs,B112-00-00      ,15461.55
    1413    2052    2385    3340
River Rch & RM=Willow_Springs,B112-00-00      ,14353.43
    1458    2116    2460    3445
River Rch & RM=Willow_Springs,B112-00-00      ,13493.31
    1522    2210    2569    3597
River Rch & RM=Willow_Springs,B112-00-00      ,12298.35
    1594    2314    2690    3767
River Rch & RM=Willow_Springs,B112-00-00      ,11014.28
    1617    2348    2730    3822
River Rch & RM=Willow_Springs,B112-00-00      ,10610.83
    1675    2432    2827    3959
River Rch & RM=Willow_Springs,B112-00-00      ,9638.195
    1860    2781    3264    4659
River Rch & RM=Willow_Springs,B112-00-00      ,8821.352
    1955    2922    3429    4875
River Rch & RM=Willow_Springs,B112-00-00      ,7798.68
    1974    2951    3462    4919
River Rch & RM=Willow_Springs,B112-00-00      ,7597.597
    2069    3091    3625    5131
River Rch & RM=Willow_Springs,B112-00-00      ,6639.987
    2170    3242    3800    5359
River Rch & RM=Willow_Springs,B112-00-00      ,5658.061
    2224    3323    3895    5481
River Rch & RM=Willow_Springs,B112-00-00      ,5148.595
    2305    3444    4035    5663
River Rch & RM=Willow_Springs,B112-00-00      ,4410.717
    2406    3594    4209    5888
River Rch & RM=Willow_Springs,B112-00-00      ,3531.853
    2535    3787    4433    6175
River Rch & RM=Willow_Springs,B112-00-00      ,2454.362
    2661    3973    4650    6452
River Rch & RM=Willow_Springs,B112-00-00      ,1246.85
    2741    4092    4788    6628
River Rch & RM=B112-00-00,B112-00-00_0009            ,17790.53
     664     964    1120    1569
River Rch & RM=B112-00-00,B112-00-00_0009            ,17677.84
     709    1030    1197    1676
River Rch & RM=B112-00-00,B112-00-00_0009            ,17517.84
    1046    1519    1766    2473
River Rch & RM=B112-00-00,B112-00-00_0009            ,16576.1
    1216    1766    2053    2875
River Rch & RM=B112-00-00,B112-00-00_0009            ,15461.55
    1413    2052    2385    3340
River Rch & RM=B112-00-00,B112-00-00_0009            ,14353.43
    1458    2116    2460    3445
River Rch & RM=B112-00-00,B112-00-00_0009            ,13493.31
    1522    2210    2569    3597
River Rch & RM=B112-00-00,B112-00-00_0009            ,12298.35
    1594    2314    2690    3767
River Rch & RM=B112-00-00,B112-00-00_0009            ,11014.28
    1617    2348    2730    3822
River Rch & RM=B112-00-00,B112-00-00_0009            ,10610.83
    1675    2432    2827    3959
River Rch & RM=B112-00-00,B112-00-00_0009            ,9638.195
    1860    2781    3264    4659
River Rch & RM=B112-00-00,B112-00-00_0009            ,8821.352
    1955    2922    3429    4875
River Rch & RM=B112-00-00,B112-00-00_0009            ,7798.68
    1974    2951    3462    4919
River Rch & RM=B112-00-00,B112-00-00_0009            ,7597.597
    2069    3091    3625    5131
River Rch & RM=B112-00-00,B112-00-00_0009            ,6639.987
    2170    3242    3800    5359
River Rch & RM=B112-00-00,B112-00-00_0009            ,5658.061
    2224    3323    3895    5481
River Rch & RM=B112-00-00,B112-00-00_0009            ,5148.595
    2305    3444    4035    5663
River Rch & RM=B112-00-00,B112-00-00_0009            ,4410.717
    2406    3594    4209    5888
River Rch & RM=B112-00-00,B112-00-00_0009            ,3531.853
    2535    3787    4433    6175
River Rch & RM=B112-00-00,B112-00-00_0009            ,2454.362
    2661    3973    4650    6452
River Rch & RM=B112-00-00,B112-00-00_0009            ,1246.85
    2741    4092    4788    6628
Boundary for River Rch & Prof#=B112-00-00,B112-00-00_0009            , 1
Up Type= 0
Dn Type= 3
Dn Slope=.00232
DSS Import GetInterval= 0
DSS Import GetPeak= 0
DSS Import FillOption= 0

--- B112-00-00.g02 (geometry) ---

Geom Title=B112-00-00 June 2007
Program Version=3.11

River Reach=B112-00-00      ,B112-00-00_0009
Reach XY= 30
        3199273.       13815804.        3201829.       13815937.
       3201888.5       13815838.      3202006.25       13814172.
       3203672.5       13814224.      3203784.75       13812918.
      3203857.75       13812877.        3204731.       13812917.
      3204803.75       13812845.      3204986.25       13809562.
      3204975.75       13809321.        3204888.       13809096.
       3204942.5       13807847.      3204383.75       13806083.
      3203917.25       13805844.        3203745.       13805271.
       3203856.5       13804790.        3203856.       13804428.
       3203616.5       13803970.        3203646.       13803359.
       3203699.5       13803229.      3203969.75       13803044.
        3203978.       13802696.      3203897.25       13802461.
      3203633.25       13802281.      3203124.25       13801685.
      3202868.25       13801592.       3202763.5       13801493.
       3202047.5       13800520.      3201954.75       13800255.

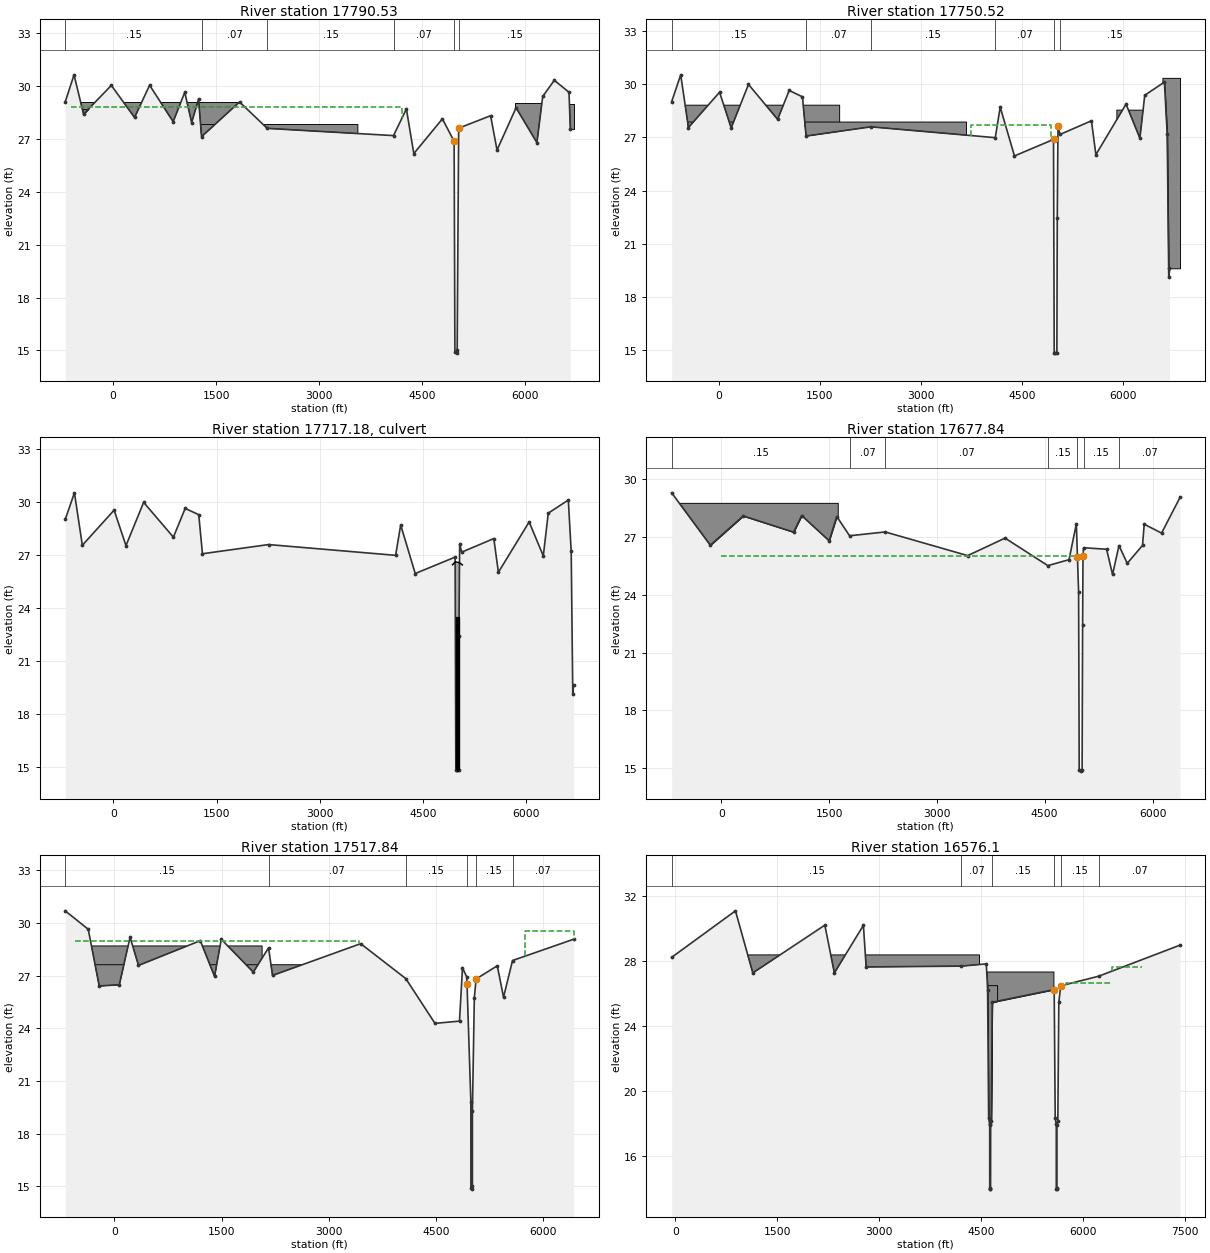
Type RM Length L Ch R = 1 ,17790.53,40.09,40.01,40
XS GIS Cut Line= 6
     3201790.105    13819827.542      3202339.39    13815070.246
     3202440.032     13814198.59     3202442.103    13814132.304
     3202461.295    13813556.053     3201819.688     13812728.38
#Sta/Elev= 30
 -697.58   29.11 -568.99   30.65 -430.42   28.42  -25.64   30.05  312.45   28.23
   531.8   30.06  874.83   27.99 1043.96   29.66 1144.04   27.94 1244.74   29.27
 1288.67   27.14 1841.62   29.11 2245.01   27.61 4084.13    27.2 4271.74   28.71
 4379.81   26.18 4795.88   28.15 4966.84   26.88 4978.29   14.91 5002.38   14.85
 5011.17   15.01 5033.16   27.62 5498.44   28.33 5591.76   26.38 5869.21   28.78
  6172.8    26.8 6257.15   29.42 6425.87   30.34 6640.17   29.66 6658.89    27.6
#Mann= 6 ,-1 , 0
 -697.58     .15       0 1288.67     .07       0 2245.01     .15       0
 4084.13     .07       0 4966.84    .015       0 5033.16     .15       0
#XS Ineff= 2 ,-1
 -614.24 4207.81   28.82 4291.79 4792.37   28.12
Permanent Ineff=
       F       F
#Block Obstruct= 4 ,-1
 -872.58 1857.79   29.08 -816.34 3564.91   27.83 -624.51  -40.42   28.71
 5861.08 6706.08   29.02
Bank Sta=4966.84,5033.16
XS Rating Curve= 0
Exp/Cntr=0.5,0.3

Type RM Length L Ch R = 1 ,17750.52,76.5,72.68,74.18
XS GIS Cut Line= 6
     3201830.129    13819829.638     3202379.126    13815074.834
     3202479.961    13814201.513     3202482.082    13814133.594
     3202501.753    13813542.956     3201851.301    13812703.873
#Sta/Elev= 30
 -698.38   29.01 -564.27   30.52  -449.5   27.55   12.29   29.54  184.59   27.53
  441.28   29.98  873.55   28.01 1045.27   29.64 1242.05   29.28 1295.87   27.07
 2256.06   27.59 4102.59   26.98 4176.12    28.7 4387.47   25.95 4966.84   26.88
 4977.38   14.85 4990.01   14.84 5016.82   14.85  5022.7   22.43 5033.16   27.62
 5062.78   27.16 5529.58   27.93 5595.68   26.02 6042.87   28.87 6248.27   26.95
 6320.64   29.37 6612.08   30.11 6653.79    27.2 6676.81   19.14 6687.73   19.62
#Mann= 6 ,-1 , 0
 -698.38     .15       0 1295.87     .07       0 2256.06     .15       0
 4102.59     .07       0 4966.84    .015       0 5062.78     .15       0
#XS Ineff= 1 ,-1
 3740.31 4935.24   27.69
Permanent Ineff=
       F
#Block Obstruct= 5 ,-1
 -854.38 1794.08   28.81 -779.57 3675.13   27.86  276.69 2903.56    24.2
    5907 6715.27   28.53 6582.79 6843.55   30.35
Bank Sta=4966.84,5033.16
XS Rating Curve= 0
Exp/Cntr=0.5,0.3

Type RM Length L Ch R = 2 ,17717.18,,,
Node Photo=G:\C2001-041 Harris County FEMA\1-Armand Bayou\Willow Springs Bayou\Survey info\Luella - 3001\3119P08.JPG
BEGIN DESCRIPTION:
Willow Springs @ Luella
END DESCRIPTION:
Bridge Culvert--1,0,-1,-1, 0
Deck Dist Width WeirC Skew NumUp NumDn MinLoCord MaxHiCord MaxSubmerge Is_Ogee
11,50,2.6,0, 4, 4, , , 0.95, 0, 0,0,,
4929.9264970.8665030.7095071.554
 26.4451 26.6122  26.561 26.4372
       0       0       0       0
4929.9264970.8665030.7095071.554
 26.4451 26.6122  26.561 26.4372
       0       0       0       0
BR Coef= 1 , 0 , 0 ,, 0 ,,,0.8,0,,1,
WSPro=,,,, 1 ,,,, 0 ,,,, 0 ,,,,-1 ,-1 ,-1 , 0 , 0 , 0 , 0 , 0
Multiple Barrel Culv=2,8.6,8.6,50,0.012,0.5,1,58,1,14.88,14.88, 2,Culvert #1  , 0 ,11
4986.9524986.9525012.8425012.842
Culvert Bottom n=0.012
Multiple Barrel Culv=2,6.6,7,50,0.012,0.5,1,58,1,14.76,14.76, 2,Culvert #2  , 0 ,11
4995.1414995.1415003.6475003.647
Culvert Bottom n=0.012
BC Design=,, 0 ,, 0 ,,,,,,
BC HTab HWMax=30.52

Type RM Length L Ch R = 1 ,17677.84,160.01,160,160.03
XS GIS Cut Line= 4
     3202230.831    13819850.617     3202506.025    13815007.208
     3202584.223    13813630.923     3202609.078    13812789.026
#Sta/Elev= 30
 -689.42    29.3 -152.49   26.58  305.84    28.1 1007.28   27.26 1119.34   28.12
 1501.44   26.81 1607.41   28.07 1785.79   27.07 2280.83   27.27 3428.56   26.04
 3949.05   26.95 4543.86   25.52 4838.76   25.83 4940.66   27.69    4956  25.953
 4971.84   24.16 4980.43    14.9 5007.38   14.85 5020.67   14.91  5027.7   22.43
    5033      26 5040.45   26.45 5361.26   26.37 5444.22   25.06 5533.94   26.56
 5648.79   25.64 5861.17   26.57 5884.76   27.67 6126.21   27.21 6382.58   29.06
#Mann= 7 ,-1 , 0
 -689.42     .15       0 1785.79     .07       0 2280.83     .07       0
 4543.86     .15       0    4956    .015       0 5040.45     .15       0
 5533.94     .07       0
#XS Ineff= 2 , 0
       0    4956      26    5033       0      26
Permanent Ineff=
       F       F
#Block Obstruct= 1 ,-1
 -863.48 1621.16   28.78
Bank Sta=4956,5033
XS Rating Curve= 0
Exp/Cntr=0.5,0.3

Type RM Length L Ch R = 1 ,17517.84,945.83,941.74,898.15
XS GIS Cut Line= 5
     3202390.614    13819858.982     3202665.768    13815016.284
     3202745.311     13813616.32     3202772.915    13813130.481
     3202611.165    13812789.931
#Sta/Elev= 30
 -689.54    30.7  -367.1   29.65 -213.24   26.42   68.17   26.49  218.82    29.2
  336.32   27.59  1201.8      29 1401.43   26.97 1495.47   29.08 1943.69   27.21
 2157.02   28.59 2213.04   27.02 3446.94   28.83 4078.43   26.84 4487.22   24.29
 4830.43   24.42 4872.19   27.46  4932.4   26.92 4935.66   26.55 4989.41   19.83
 4989.97   14.92 5002.38   14.85 5011.17   15.01 5011.27   19.29    5038   25.75
 5062.86   26.82  5359.5   27.57 5446.83   25.78 5572.87   27.87 6426.83   29.08
#Mann= 6 ,-1 , 0
 -689.54     .15       0 2157.02     .07       0 4078.43     .15       0
  4932.4    .015       0 5062.86     .15       0 5572.87     .07       0
#XS Ineff= 3 ,-1
  -551.5 3422.43      29 5748.07 6508.27   29.54 3422.43    4900      27
Permanent Ineff=
       F       F       F
#Block Obstruct= 2 ,-1
 -799.77 2067.12    28.7 -763.37 3596.13   27.63
Bank Sta=4935.66,5062.86
XS Rating Curve= 0
Exp/Cntr=0.3,0.1

Type RM Length L Ch R = 1 ,16576.1 ,1240.48,1114.55,938.06
XS GIS Cut Line= 5
     3203253.314    13819876.883     3203657.179    13814262.621
     3203650.934    13814195.028     3203430.122    13813588.134
     3202614.785    13812793.551
#Sta/Elev= 30
  -53.38   28.21  885.47   31.07  1140.5   27.25 2200.95   30.19 2340.91   27.25
 2768.28   30.18 2808.86   27.62 4210.76   27.67 4577.17   27.81 4596.06   26.23
 4611.19   18.32 4626.98   17.94 4627.57   13.97 4631.03   13.96 4634.33      14
 4634.93    17.9 4649.61   18.14 4663.94   25.45 5576.06   26.23 5591.19   18.32
 5606.98   17.94 5607.57   13.97 5611.03   13.96 5614.33      14 5614.93    17.9
 5629.61   18.14 5643.94   25.45 5672.56   26.46 6230.62   27.05 7427.57   28.96
#Mann= 6 ,-1 , 0
  -53.38     .15       0 4210.76     .07       0 4663.94     .15       0
 5576.06    .015       0 5672.56     .15       0 6230.62     .07       0
#XS Ineff= 2 ,-1
 5746.49 6408.46   26.61  6424.9 6873.33   27.63
Permanent Ineff=
       F       F
#Block Obstruct= 3 ,-1
   725.6 4476.46   28.36 4516.75 5564.87   27.34 4566.77 4735.89    26.5
Bank Sta=5576.06,5672.56
XS Rating Curve= 0
Exp/Cntr=0.3,0.1

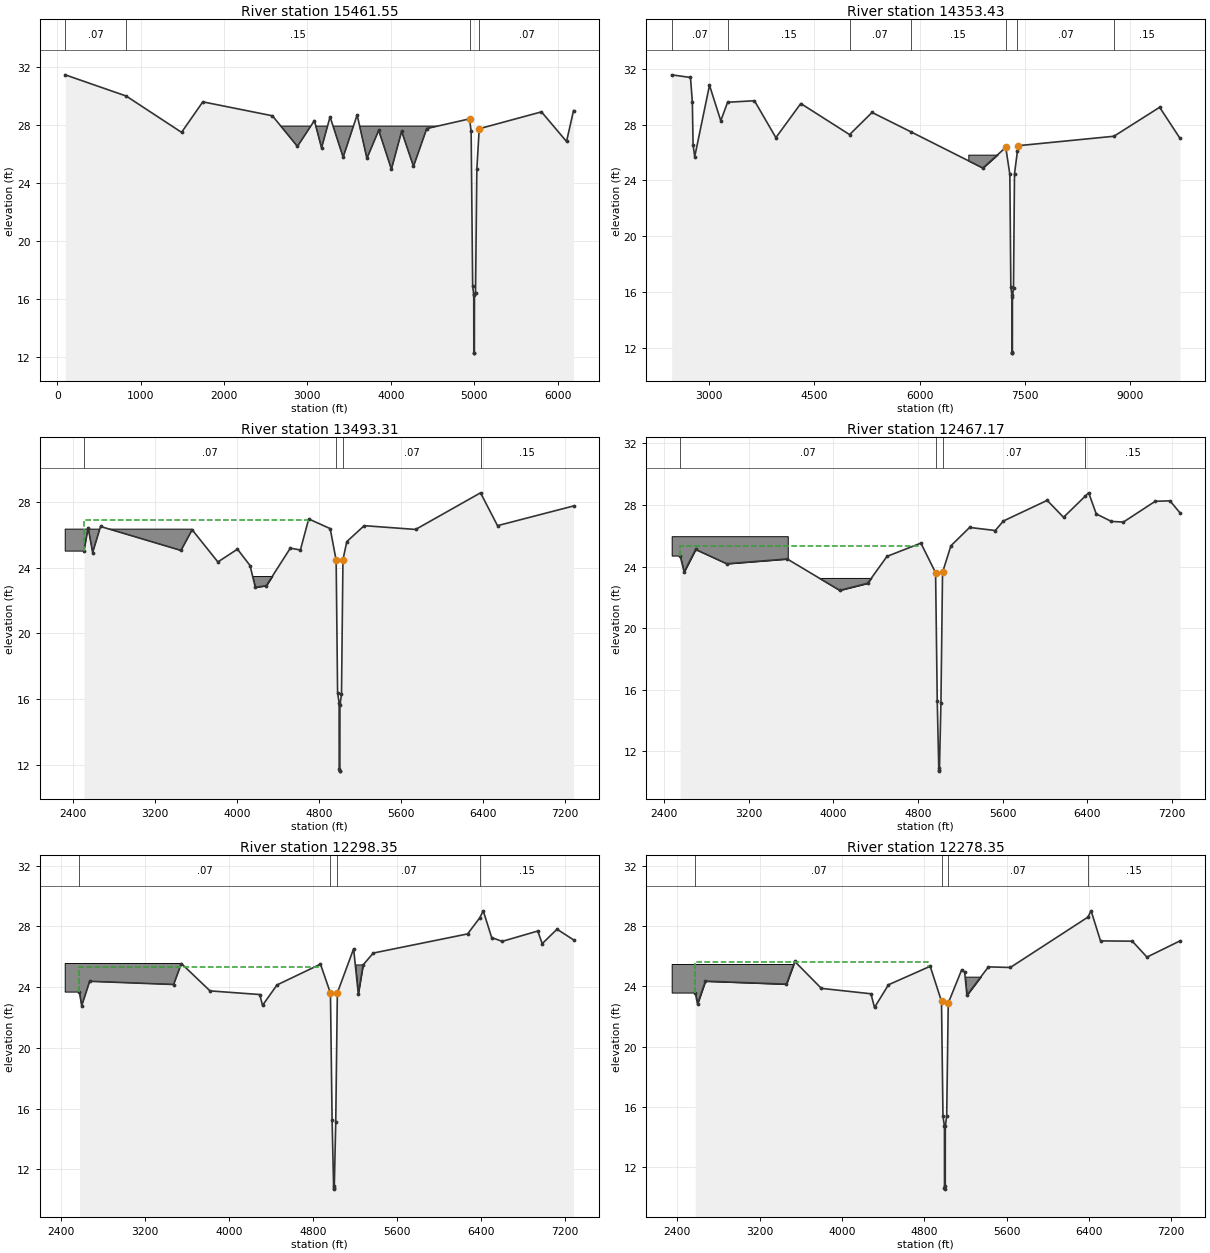
Type RM Length L Ch R = 1 ,15461.55,928.84,1108.12,1203.95
XS GIS Cut Line= 5
     3205006.868    13817735.249     3204273.825     13813581.34
     3203785.177    13813143.899      3203720.33    13813138.892
     3202615.838    13812792.406
#Sta/Elev= 30
   95.33   31.44  826.92   29.98 1490.85   27.48 1745.81   29.58 2580.54   28.62
 2880.46   26.51 3083.89   28.29  3169.9   26.41 3271.99   28.55 3428.82   25.77
 3596.56   28.68 3713.83   25.69 3855.52   27.62 4007.61   24.94 4130.21   27.55
 4272.41   25.14 4431.69   27.74 4944.95   28.41 4963.86   27.54  4982.1   16.88
 4995.22    16.3 4995.96   12.28 5002.65   12.31 5003.67   16.36 5016.44   16.43
 5032.13   24.93 5060.65   27.73 5807.36   28.89 6108.04   26.85 6191.87   28.98
#Mann= 4 ,-1 , 0
   95.33     .07       0  826.92     .15       0 4944.95    .015       0
 5060.65     .07       0
#Block Obstruct= 1 ,-1
 2234.21 4854.19   27.91
Bank Sta=4944.95,5060.65
XS Rating Curve= 0
Exp/Cntr=0.3,0.1

Type RM Length L Ch R = 1 ,14353.43,1022.39,860.12,710.89
XS GIS Cut Line= 5
     3205035.614    13817749.622     3204650.052    13812948.663
     3204651.923    13812884.439     3204405.365    13812458.905
     3202570.368    13812099.605
#Sta/Elev= 30
 2468.81   31.58 2736.79   31.39 2763.24   29.64 2773.76   26.55 2796.99    25.7
 3007.66   30.83 3168.44   28.28 3265.46   29.61 3648.19   29.72 3953.49   27.07
 4308.35   29.52 5003.62   27.29  5323.8   28.88  5872.7    27.5 6902.25   24.89
 7228.69   26.37 7286.79   24.44 7300.91   16.37 7315.68   15.76  7316.3    11.7
 7319.96    11.6 7323.17   11.62 7323.84   15.64 7338.99   16.27 7353.21   24.48
 7395.76   26.14 7400.81   26.49 8769.62   27.17    9421   29.25 9711.12   27.02
#Mann= 7 ,-1 , 0
 2468.81     .07       0 3265.46     .15       0 5003.62     .07       0
  5872.7     .15       0 7228.69    .015       0 7395.76     .07       0
 8769.62     .15       0
#Block Obstruct= 1 ,-1
 6695.22 7190.69   25.85
Bank Sta=7228.69,7400.81
XS Rating Curve= 0
Exp/Cntr=0.3,0.1

Type RM Length L Ch R = 1 ,13493.31,1026.04,1026.14,1020.05
XS GIS Cut Line= 4
     3207316.294    13812459.247     3204869.989    13812174.558
     3204803.651    13812171.361     3202557.536    13812018.848
#Sta/Elev= 30
 2504.57      25 2544.98   26.43 2588.75   24.91 2665.79    26.5 3451.65   25.04
  3560.5    26.3 3812.05   24.34    4003   25.12 4126.07   24.12 4177.17   22.79
 4285.17    22.9 4519.22   25.18 4617.54   25.07  4698.6   26.96 4908.69   26.37
 4966.79   24.44 4980.91   16.37 4995.68   15.76  4996.3    11.7 4999.96    11.6
 5003.17   11.62 5003.84   15.64 5018.99   16.27 5033.21   24.48 5071.08   25.58
 5240.73   26.55 5742.92   26.32 6376.79   28.55 6542.77   26.55 7285.09   27.75
#Mann= 4 ,-1 , 0
 2504.57     .07       0 4966.79    .015       0 5033.21     .07       0
 6376.79     .15       0
#XS Ineff= 2 , 0
       0    4691    26.9               0
Permanent Ineff=
       F       F
#Block Obstruct= 2 ,-1
 2320.73 3556.71   26.34  4121.7 4411.02   23.48
Bank Sta=4966.79,5033.21
XS Rating Curve= 0
Exp/Cntr=0.3,0.1

Type RM Length L Ch R = 1 ,12467.17,172.1,168.82,172.63
XS GIS Cut Line= 4
     3207328.527    13811407.183     3204926.078    13811150.214
     3204860.374    13811146.433     3202618.703     13811211.45
#Sta/Elev= 30
 2552.67   24.71 2590.25   23.64 2699.23   25.11 2993.14   24.18 3565.17   24.49
 4060.89   22.45 4325.09   22.91 4507.81   24.66 4828.09   25.52 4967.09    23.6
 4982.85   15.23 4997.21   10.88  5000.7    10.7  5003.6    10.8 5017.62    15.1
 5032.91   23.62 5112.12   25.35 5288.96   26.54 5531.21   26.34 5608.11   26.96
 6021.87    28.3 6176.37    27.2 6379.58   28.56 6414.11   28.79 6485.58   27.42
  6629.3   26.93 6742.42   26.89 7043.13   28.24 7182.37   28.27 7277.25   27.49
#Mann= 4 ,-1 , 0
 2552.67     .07       0 4967.09    .015       0 5032.91     .07       0
 6379.58     .15       0
#XS Ineff= 2 , 0
       0 4816.17   25.35               0
Permanent Ineff=
       F       F
#Block Obstruct= 2 ,-1
 2472.66 3569.91   25.97 3797.93 4431.69   23.26
Bank Sta=4967.09,5032.91
XS Rating Curve= 0
Exp/Cntr=0.3,0.1

Type RM Length L Ch R = 1 ,12298.35,20,20,20.01
XS GIS Cut Line= 2
     3207327.904    13811073.751     3202618.773    13810891.411
#Sta/Elev= 30
 2572.98   23.67 2594.74   22.77 2670.52   24.38 3471.54   24.17 3545.45   25.55
 3818.71   23.75 4292.26   23.51 4319.59    22.8 4457.12   24.14 4872.16   25.51
 4967.09    23.6 4982.85   15.23 4997.21   10.88  5000.7    10.7  5003.6    10.8
 5017.62    15.1 5032.91   23.62 5188.23   26.52 5232.42   23.56 5278.51   25.46
  5375.5   26.24  6275.1    27.5 6390.23   28.55 6424.53   29.02 6504.86   27.26
 6605.26   27.01 6944.49   27.69 6986.79   26.86 7128.14   27.81 7285.64   27.11
#Mann= 4 ,-1 , 0
 2572.98     .07       0 4967.09    .015       0 5032.91     .07       0
 6390.23     .15       0
#XS Ineff= 2 , 0
       0 4870.93   25.35               0
Permanent Ineff=
       F       F
#Block Obstruct= 2 ,-1
 2437.23 3548.05   25.55 5153.58 7285.64   25.49
Bank Sta=4967.09,5032.91
XS Rating Curve= 0
Exp/Cntr=0.5,0.3

Type RM Length L Ch R = 1 ,12278.35,89.98,89.63,89.17
BEGIN DESCRIPTION:
100 Year CANNOT be contained within left bank through xsec 13493 - WILL breach floodplain if contained
END DESCRIPTION:
XS GIS Cut Line= 2
     3207328.678    13811053.766     3202619.547    13810871.426
#Sta/Elev= 30
 2572.98   23.59 2595.52   22.83 2671.88   24.35  3460.1   24.15    3541   25.66
 3799.23   23.87 4281.29   23.51 4315.96    22.6 4451.81   24.11 4857.39   25.34
  4967.2   23.01 4981.57   15.36 4995.89   14.69 4996.25    10.6 5001.71   10.51
 5003.86   10.73  5004.1   14.68 5017.66   15.39  5032.8   22.89 5163.61   25.11
 5192.46   24.96 5213.91   23.41 5423.19    25.3 5636.36   25.26 6390.23   28.61
 6421.33   29.03 6513.03   27.03  6822.1   27.01 6964.44   25.95 7285.64   27.03
#Mann= 4 ,-1 , 0
 2572.98     .07       0  4967.2    .015       0  5032.8     .07       0
 6390.23     .15       0
#XS Ineff= 2 , 0
       0 4839.63    25.6               0
Permanent Ineff=
       F       F
#Block Obstruct= 2 ,-1
  2344.2 3548.89   25.49 5165.99 7285.64   24.65
Bank Sta=4967.2,5032.8
XS Rating Curve= 0
Exp/Cntr=0.5,0.3

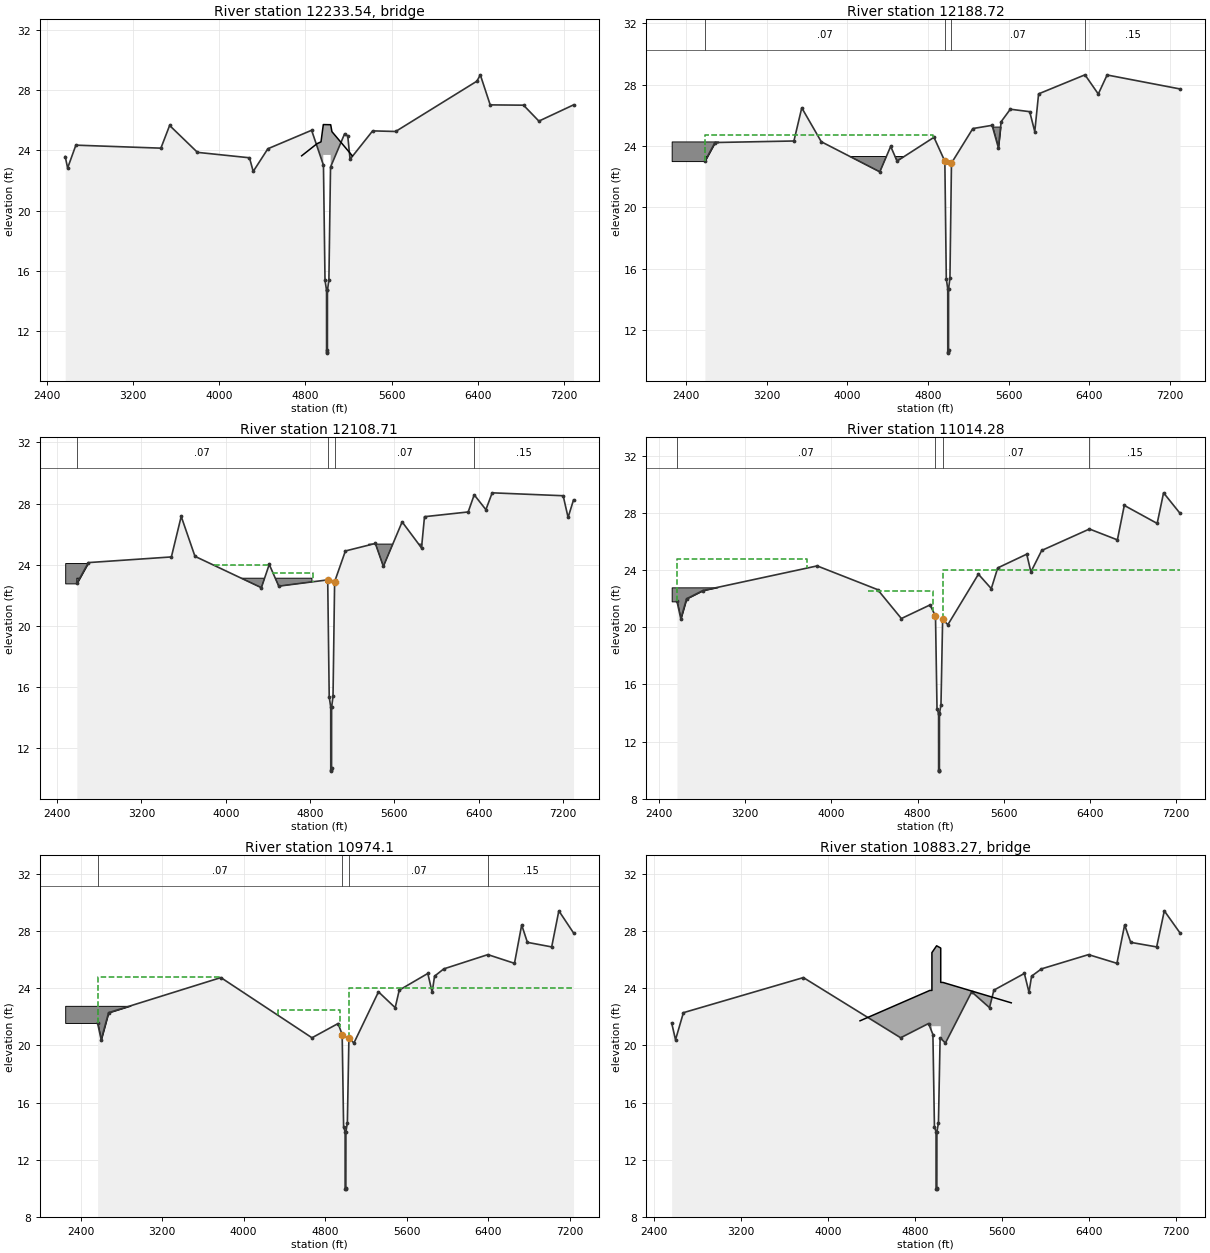
Type RM Length L Ch R = 3 ,12233.54,,,
Node Photo=G:\C2001-041 Harris County FEMA\1-Armand Bayou\Willow Springs Bayou\Survey info\Bridge in Cemetary - 3069\MVC-011S.JPG
BEGIN DESCRIPTION:
Cemetary Bridge
END DESCRIPTION:
Bridge Culvert--1,0,-1,-1, 0
Deck Dist Width WeirC Skew NumUp NumDn MinLoCord MaxHiCord MaxSubmerge Is_Ogee
16,8.5,2.6,0, 9, 9, , , 0.95, 0, 0,0,,
    4765    4908 4944.44 4965.82 4965.83 5034.39  5034.4 5045.67    5235
   23.64   24.45   24.57   25.72   25.72   25.71   25.71   25.25   23.64
       0       0       0       0    23.7    23.7       0       0       0
    4765    4908 4944.44 4965.82 4965.83 5034.39  5034.4 5045.67    5235
   23.64   24.45   24.57   25.72   25.72   25.71   25.71   25.25   23.64
       0       0       0       0    23.7    23.7       0       0       0
BR Coef=-1 , 0 , 0 ,, 0 ,,,0.8,0,,0,
WSPro=,,,, 1 ,,,, 0 ,,,, 0 ,,,,-1 ,-1 ,-1 , 0 , 0 , 0 , 0 , 0
BC Design=,, 0 ,, 0 ,,,,,,
BC HTab HWMax=29.03

Type RM Length L Ch R = 1 ,12188.72,80.03,80.01,80.06
XS GIS Cut Line= 4
      3207320.75    13810942.777     3204941.058    13810871.651
      3204875.51    13810869.068     3202611.619    13810800.076
#Sta/Elev= 30
 2587.82   23.02  2688.2   24.23 3470.48   24.33  3548.2   26.49 3742.07   24.28
 4322.22   22.32 4430.13   23.98 4493.26   23.02 4859.19   24.57  4967.2   23.01
 4981.57   15.36 4995.89   14.69 4996.25    10.6 5001.71   10.51 5003.86   10.73
  5004.1   14.68 5017.66   15.39  5032.8   22.89  5244.7   25.14 5435.58   25.35
 5497.79   23.89 5525.74   25.59 5616.34    26.4 5808.61   26.24 5858.91   24.94
 5896.84    27.4 6356.86   28.64 6488.81   27.39 6576.19   28.63 7299.12   27.72
#Mann= 4 ,-1 , 0
 2587.82     .07       0  4967.2    .015       0  5032.8     .07       0
 6356.86     .15       0
#XS Ineff= 2 , 0
       0 4847.46    24.7               0
Permanent Ineff=
       F       F
#Block Obstruct= 3 ,-1
 2258.15 2719.69    24.3 2595.62 4866.15   23.32 5363.75 5692.31   25.27
Bank Sta=4967.2,5032.8
XS Rating Curve= 0
Exp/Cntr=0.5,0.3

Type RM Length L Ch R = 1 ,12108.71,1089.89,1094.43,1102.07
XS GIS Cut Line= 4
      3207323.14    13810862.812     3204943.828    13810791.698
     3204878.303    13810789.116     3202614.056    13810720.113
#Sta/Elev= 30
 2587.84   22.78  2697.5   24.14 3484.38   24.51 3577.57   27.16 3708.03   24.55
 4338.04    22.5 4412.67   24.02 4502.91    22.6  4967.2   23.01 4981.57   15.36
 4995.89   14.69 4996.25    10.6 5001.71   10.51 5003.86   10.73  5004.1   14.68
 5017.66   15.39  5032.8   22.89 5135.11    24.9 5419.28   25.39 5495.21   23.89
 5673.24    26.8 5857.12    25.1 5885.41   27.14 6299.77   27.45 6356.84   28.57
 6467.82    27.6  6527.5    28.7 7200.72   28.51 7247.47   27.09 7299.09   28.24
#Mann= 4 ,-1 , 0
 2587.84     .07       0  4967.2    .015       0  5032.8     .07       0
 6356.84     .15       0
#XS Ineff= 2 ,-1
 3889.47 4409.74   23.97 4436.42  4823.3   23.48
Permanent Ineff=
       F       F
#Block Obstruct= 3 ,-1
 2477.18 2696.22   24.11 2587.85  4817.8   23.12 5355.93 6756.19   25.35
Bank Sta=4967.2,5032.8
XS Rating Curve= 0
Exp/Cntr=0.3,0.1

Type RM Length L Ch R = 1 ,11014.28,40,40.18,40.94
XS GIS Cut Line= 4
     3207398.838    13809858.709      3205002.19    13809701.783
     3204937.147    13809691.979     3202735.309    13809593.304
#Sta/Elev= 30
 2566.09    21.8  2601.5   20.58 2654.86   21.98  2807.2   22.56 3867.85   24.28
 4429.88   22.62 4649.93    20.6 4915.97   21.55  4966.9   20.77 4981.01   14.28
 4995.78   13.96 4995.85    9.97 5000.36    9.93 5003.16    9.98 5003.64   13.95
 5017.82   14.57  5033.1   20.54  5081.9   20.17  5365.6    23.7 5485.09   22.69
 5544.63   24.14 5814.17    25.1 5852.98   23.86 5953.19   25.36 6396.81   26.86
 6656.26    26.1 6720.28   28.51 7025.82   27.25 7085.03   29.39  7237.7   27.96
#Mann= 4 ,-1 , 0
 2566.09     .07       0  4966.9    .015       0  5033.1     .07       0
 6396.81     .15       0
#XS Ineff= 3 ,-1
  2390.1 3775.14   24.77 4338.98 4941.33    22.5  5033.1  7238.1      24
Permanent Ineff=
       F       F       F
#Block Obstruct= 1 ,-1
 2516.65 3522.39   22.78
Bank Sta=4966.9,5033.1
XS Rating Curve= 0
Exp/Cntr=0.5,0.3

Type RM Length L Ch R = 1 ,10974.1 ,188.36,181.67,179.56
BEGIN DESCRIPTION:
Spencer Highway
END DESCRIPTION:
XS GIS Cut Line= 4
     3207401.452    13809818.795     3205006.485    13809661.978
     3204941.034    13809652.113     3202737.099    13809553.344
#Sta/Elev= 30
 2565.67   21.58 2601.04    20.4 2673.56    22.3 3776.28   24.76 4670.52   20.54
 4926.81   21.54  4966.9   20.77 4981.01   14.28 4995.78   13.96 4995.85    9.97
 5000.36    9.93 5003.16    9.98 5003.64   13.95 5017.82   14.57  5033.1   20.54
  5081.9   20.17 5323.36   23.76 5487.29   22.65 5527.22   23.88 5807.55   25.05
 5850.19   23.73 5873.87   24.86 5964.39   25.37 6397.06   26.37 6658.46   25.76
 6729.21   28.45 6785.12   27.23 7023.59   26.91  7093.9   29.44  7238.1   27.89
#Mann= 4 ,-1 , 0
 2565.67     .07       0  4966.9    .015       0  5033.1     .07       0
 6397.06     .15       0
#XS Ineff= 3 ,-1
  2390.1 3775.14   24.77 4338.98 4941.33    22.5  5033.1  7238.1      24
Permanent Ineff=
       F       F       F
#Block Obstruct= 1 ,-1
 2247.99 3487.94   22.78
Bank Sta=4966.9,5033.1
XS Rating Curve= 0
Exp/Cntr=0.5,0.3

Type RM Length L Ch R = 3 ,10883.27,,,
Node Photo=G:\C2001-041 Harris County FEMA\1-Armand Bayou\Willow Springs Bayou\Survey info\Spencer - 3070\MVC-040S.JPG
BEGIN DESCRIPTION:
Spencer Highway
END DESCRIPTION:
Bridge Culvert--1,0,-1,-1, 0
Deck Dist Width WeirC Skew NumUp NumDn MinLoCord MaxHiCord MaxSubmerge Is_Ogee
47,99,2.6,0, 9, 9, , , 0.95, 0, 0,0,,
    4297 4938.52 4957.71 4957.71  5000.9 5038.81 5038.81 5059.17    5687
   21.73   23.86   23.86   26.51   26.99   26.83   24.42   24.42   22.99
       0       0       0   21.35   21.35   21.35       0       0       0
    4297 4938.52 4957.71 4957.71  5000.9 5038.81 5038.81 5059.17    5687
   21.73   23.86   23.86   26.51   26.99   26.83   24.42   24.42   22.99
       0       0       0   21.35   21.35   21.35       0       0       0
BR Coef=-1 , 0 , 0 ,, 0 ,,,0.8,0,,0,
WSPro=,,,, 1 ,,,, 0 ,,,, 0 ,,,,-1 ,-1 ,-1 , 0 , 0 , 0 , 0 , 0
BC Design=,, 0 ,, 0 ,,,,,,
BC HTab HWMax=29.44