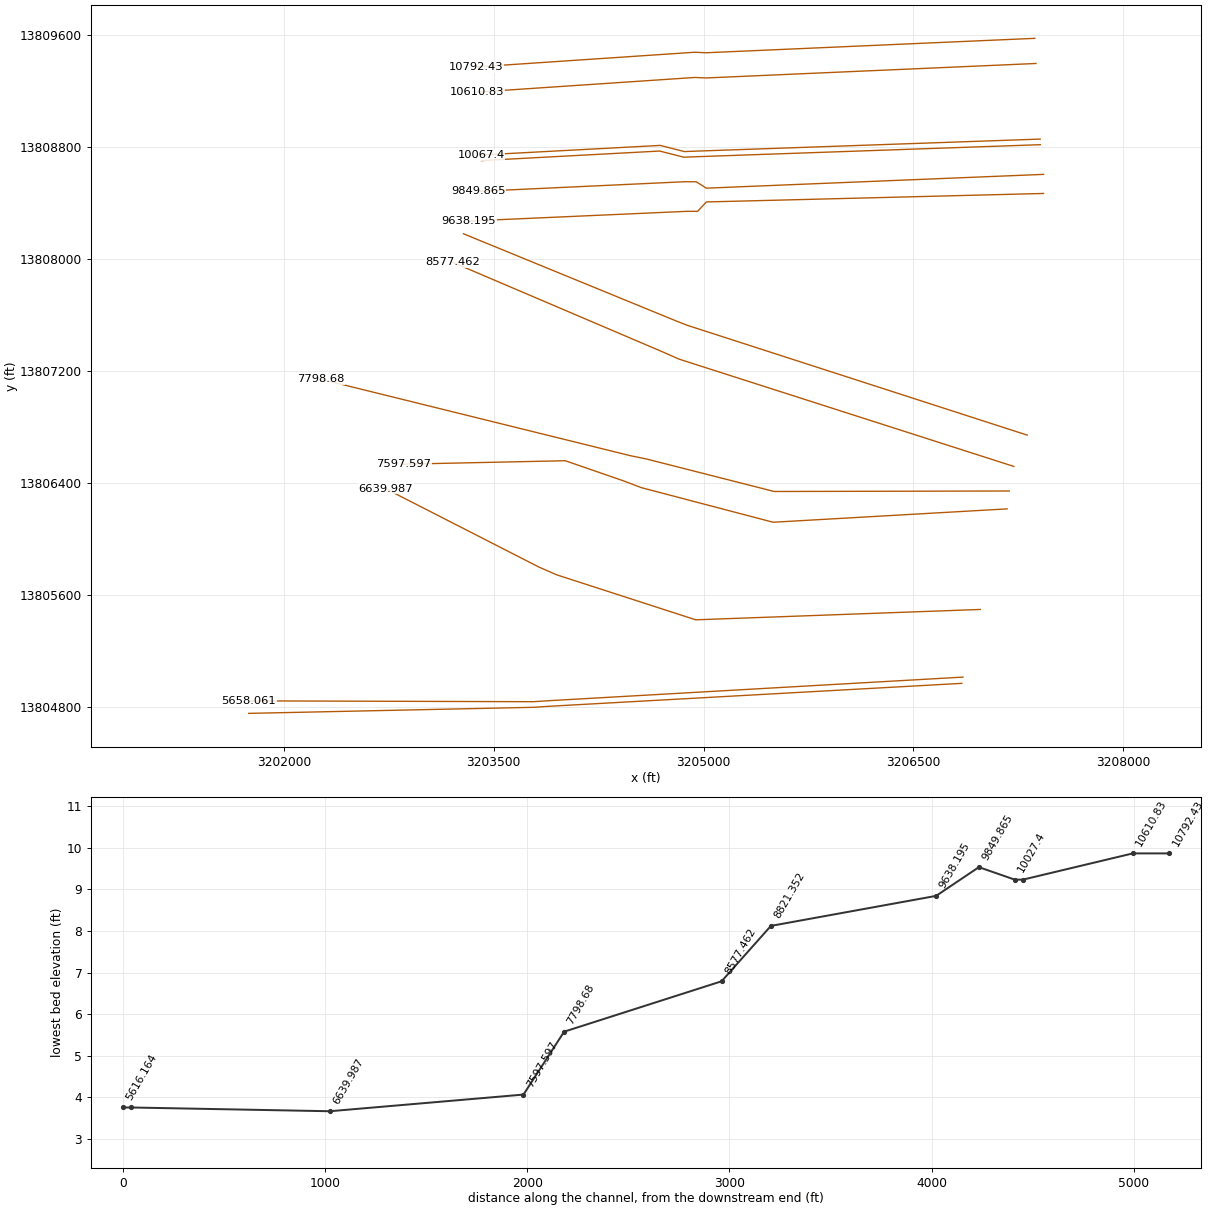
HEC-RAS study B112-00-00.prj: B112-00-00

--- B112-00-00.g02 (geometry) --- (continued)

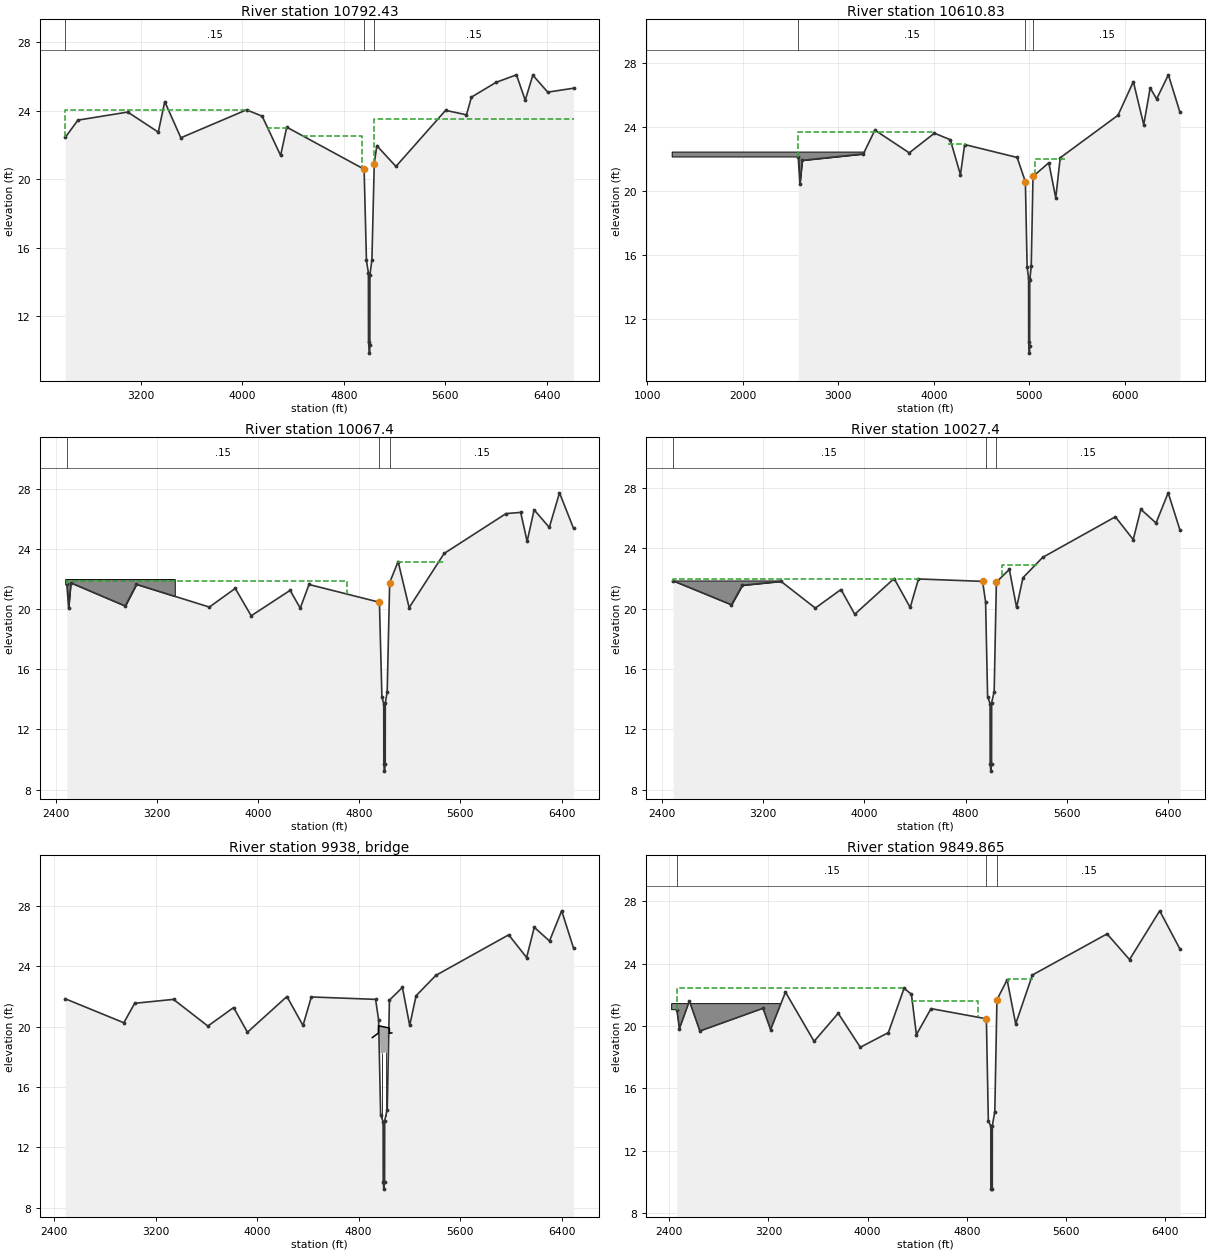
Type RM Length L Ch R = 1 ,10792.43,180.08,181.6,185.2
BEGIN DESCRIPTION:
Spencer Highway
END DESCRIPTION:
XS GIS Cut Line= 4
     3207369.361    13809578.137     3205017.617    13809474.951
     3204937.302    13809478.699     3203371.495    13809373.309
#Sta/Elev= 30
 2605.75   22.43 2706.19   23.44 3098.16   23.91 3338.97   22.74 3389.71   24.52
 3516.69   22.41 4034.22   24.04 4157.07   23.67 4302.45   21.38 4350.63   23.03
 4960.03   20.58  4978.4   15.27 4993.69   14.54 4994.59   10.53 5002.45    9.86
 5005.28   10.31 5006.03   14.44 5021.45   15.29 5039.97   20.91 5060.25   21.95
 5210.64   20.74 5601.74   24.01 5766.41   23.75 5805.33   24.78 5999.03   25.64
 6159.95   26.08 6228.99    24.6 6289.12   26.06 6406.21   25.07 6609.51    25.3
#Mann= 3 ,-1 , 0
 2605.75     .15       0 4960.03    .015       0 5039.97     .15       0
#XS Ineff= 4 ,-1
 2436.77 4053.46   24.02 4206.91    4352   22.99 4470.67 4946.54    22.5
 5039.97 6609.51    23.5
Permanent Ineff=
       F       F       F       F
#Block Obstruct= 1 ,-1
 2364.64 4108.15   19.49
Bank Sta=4960.03,5039.97
XS Rating Curve= 0
Exp/Cntr=0.5,0.3

Type RM Length L Ch R = 1 ,10610.83,521.5,543.42,508.76
XS GIS Cut Line= 4
     3207377.252     13809398.31     3205017.366    13809294.767
     3204939.157    13809298.417     3203383.583    13809193.715
#Sta/Elev= 30
 2580.28   22.16 2598.23   20.43 2622.65   21.92 3262.25   22.32 3383.72   23.81
 3743.58   22.39 4006.98   23.62 4173.75   23.21 4279.82   21.02 4324.01   22.91
 4874.23    22.1 4960.03   20.58  4978.4   15.27 4993.69   14.54 4994.59   10.53
 5002.45    9.86 5005.28   10.31 5006.03   14.44 5021.45   15.29 5039.97   20.91
 5205.45   21.77 5278.35   19.57 5324.96   22.08  5930.1   24.74 6091.15   26.84
 6199.83   24.15  6267.6   26.45 6335.03   25.76 6458.18   27.27 6579.82   24.92
#Mann= 3 ,-1 , 0
 2580.28     .15       0 4960.03    .015       0 5039.97     .15       0
#XS Ineff= 3 ,-1
 2436.77 3994.78   23.68 4144.72 4327.25   22.94 5063.89 5370.27   22.02
Permanent Ineff=
       F       F       F
#Block Obstruct= 1 ,-1
 1254.88 3406.14   22.47
Bank Sta=4960.03,5039.97
XS Rating Curve= 0
Exp/Cntr=0.3,0.1

Type RM Length L Ch R = 1 ,10067.4 ,40.04,40,41.94
BEGIN DESCRIPTION:
Xsec extended to tributary bank on left side
END DESCRIPTION:
XS GIS Cut Line= 5
     3207407.637    13808857.641     3204939.035    13808771.249
     3204863.787    13808768.199     3204690.227    13808812.429
     3203409.963    13808743.844
#Sta/Elev= 30
 2487.85   21.64 2501.74   20.05 2519.52   21.74 2949.61    20.2 3038.12   21.64
  3614.6   20.13 3819.46   21.37 3945.46   19.55 4253.28   21.24 4333.36   20.06
 4402.74   21.63 4959.48   20.45  4979.1   14.17 4993.62    13.7 4994.34    9.68
 4999.45    9.23 5005.22    9.71 5006.01   13.77 5020.92    14.5 5040.52   21.76
 5107.38   23.15 5194.59   20.09 5471.06   23.69  5960.4   26.34 6076.58   26.42
 6127.55   24.49 6182.84   26.59 6303.01   25.42  6383.5   27.72 6494.48   25.36
#Mann= 3 ,-1 , 0
 2487.85     .15       0 4959.48    .015       0 5040.52     .15       0
#XS Ineff= 2 ,-1
 2222.22 4705.92   21.86 5109.52  5481.1   23.15
Permanent Ineff=
       F       F
#Block Obstruct= 1 ,-1
 2474.76 3340.94   21.99
Bank Sta=4959.48,5040.52
XS Rating Curve= 0
Exp/Cntr=0.5,0.3

Type RM Length L Ch R = 1 ,10027.4 ,227.21,177.54,190.22
XS GIS Cut Line= 5
     3207409.036    13808817.666     3204940.544    13808731.278
      3204859.57    13808727.995     3204686.268     13808772.16
     3203412.103    13808703.901
#Sta/Elev= 30
 2488.32   21.85 2950.24   20.26 3035.89   21.55 3341.72   21.81 3612.67   20.04
 3815.59   21.27 3924.37   19.63 4235.47      22 4362.35   20.08  4427.7   21.97
 4934.44   21.81 4958.07   20.45    4974   14.17 4993.62    13.7 4994.34    9.68
 4999.45    9.23 5005.22    9.71 5006.01   13.77 5025.92    14.5 5043.31   21.76
 5145.78    22.6 5203.13   20.08 5253.37   22.05 5408.99    23.4 5983.33   26.09
 6124.61   24.58  6184.7   26.59 6304.87   25.68 6400.69   27.68  6494.2   25.21
#Mann= 3 ,-1 , 0
 2488.32     .15       0 4958.07    .015       0 5043.31     .15       0
#XS Ineff= 2 ,-1
  2482.3  4430.7   21.98 5089.68 5368.17   22.87
Permanent Ineff=
       F       F
#Block Obstruct= 1 ,-1
 2477.72 3342.83   21.87
Bank Sta=4934.44,5043.31
XS Rating Curve= 0
Exp/Cntr=0.5,0.3

Type RM Length L Ch R = 3 ,9938    ,,,
Node Photo=G:\C2001-041 Harris County FEMA\1-Armand Bayou\Willow Springs Bayou\Survey info\Bandridge - 3126\MVC-015S.JPG
BEGIN DESCRIPTION:
Bandridge
END DESCRIPTION:
Bridge Culvert--1,0,-1,-1, 0
Deck Dist Width WeirC Skew NumUp NumDn MinLoCord MaxHiCord MaxSubmerge Is_Ogee
70,35,2.6,0, 6, 6, , , 0.95, 0, 0,0,,
 4908.64    4956 4957.38 5042.62 5043.95 5062.21
   19.28   19.57   20.06   19.91   19.56   19.59
       0       0    18.2   18.34       0       0
 4908.64    4956 4957.38 5042.62 5043.95 5062.21
   19.28   19.57   20.06   19.91   19.56   19.59
       0       0    18.2   18.34       0       0
Pier Skew, UpSta & Num, DnSta & Num=  ,4986, 4 ,4986, 4 , 3 , 3 , 0 ,,
     1.2     1.2     2.1     2.1
      10   15.84   15.84   18.34
     1.2     1.2     2.1     2.1
      10   15.84   15.84   18.34
Pier Skew, UpSta & Num, DnSta & Num=  ,5014, 4 ,5014, 4 , 3 , 3 , 0 ,,
     1.2     1.2     2.1     2.1
      10   15.84   15.84   18.34
     1.2     1.2     2.1     2.1
      10   15.84   15.84   18.34
BR Coef=-1 , 1 , 0 ,1.25, 0 ,,,0.8,0,2,0,
WSPro=,,,, 1 ,,,, 0 ,,,, 0 ,,,,-1 ,-1 ,-1 , 0 , 0 , 0 , 0 , 0
BC Design=,, 0 ,, 0 ,,,,,,
BC HTab HWMax=27.68

Type RM Length L Ch R = 1 ,9849.865,99.29,211.67,212
BEGIN DESCRIPTION:
xsec extended to tributary bank on left side, 500 not contained
END DESCRIPTION:
XS GIS Cut Line= 5
     3207431.789    13808605.305     3205019.978    13808506.709
     3204948.328    13808552.264     3204868.174    13808552.788
      3203389.35    13808483.956
#Sta/Elev= 30
  2460.9   21.05 2481.55   19.83 2562.13   21.61 2646.69   19.68 3156.12   21.14
 3217.16   19.77 3337.26   22.18 3568.07   19.02  3762.5   20.82 3941.01   18.64
  4167.3   19.58  4294.2   22.43 4353.47   22.04 4393.51   19.45 4511.46   21.12
 4958.07   20.47    4974   13.91 4993.91   13.57 4994.28    9.53 5005.58    9.53
 5005.93    13.6    5026   14.51 5043.31   21.69 5125.54   22.97 5194.54   20.14
 5329.45   23.28 5931.81   25.92 6112.96   24.27 6356.45    27.4 6520.21   24.94
#Mann= 3 ,-1 , 0
  2460.9     .15       0 4958.07    .015       0 5043.31     .15       0
#XS Ineff= 3 ,-1
  2378.1 4301.17   22.43 4353.32 4887.88    21.6 5129.07 5331.16   23.05
Permanent Ineff=
       F       F       F
#Block Obstruct= 1 ,-1
 2419.06 3320.32   21.44
Bank Sta=4958.07,5043.31
XS Rating Curve= 0
Exp/Cntr=0.5,0.3

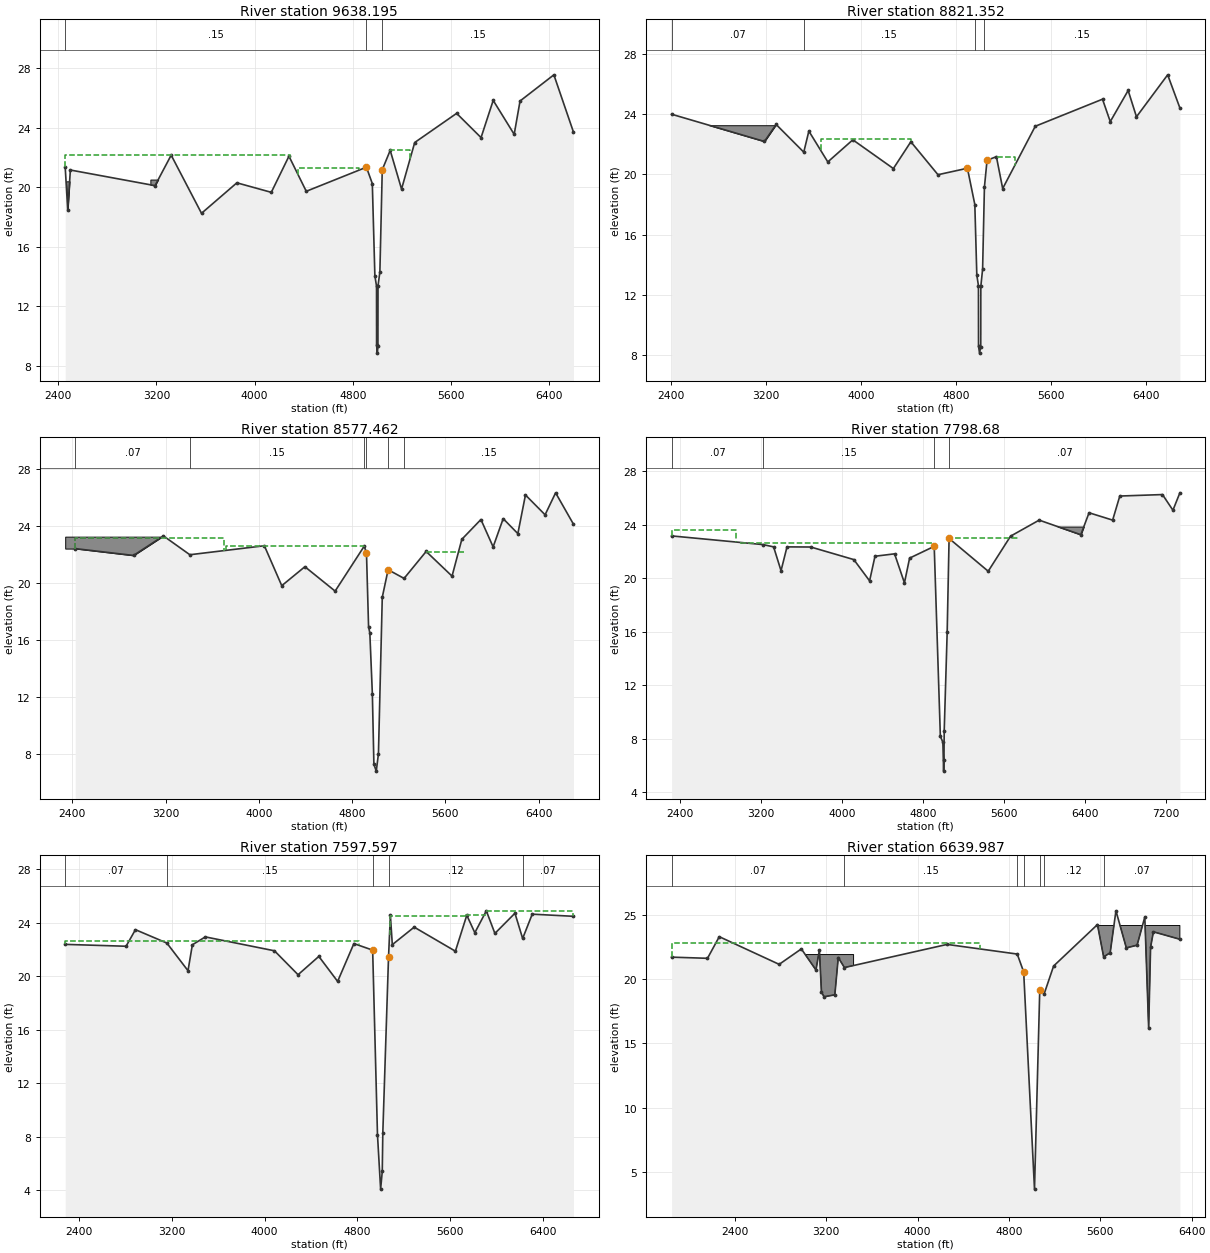
Type RM Length L Ch R = 1 ,9638.195,924.29,816.84,780.12
BEGIN DESCRIPTION:
xsec extended to tributary bank on left side, 500 not contained
END DESCRIPTION:
XS GIS Cut Line= 5
     3207431.789    13808468.787     3205019.978    13808408.113
      3204958.38    13808341.168     3204877.341    13808340.902
     3203321.091    13808271.595
#Sta/Elev= 30
 2456.58   21.34 2477.22   18.47 2498.71   21.15 3188.51    20.1 3320.22   22.15
 3567.49   18.24 3855.58   20.29 4136.18   19.65  4280.1   22.08 4421.14   19.72
 4911.36   21.34 4959.48   20.24 4980.39   14.04 4993.79   13.34 4994.38    9.36
 5000.55    8.84 5005.38    9.31 5006.03   13.37 5021.21    14.3 5040.52   21.17
 5105.31   22.47 5197.71   19.87 5305.09      23 5646.66   24.96 5845.63   23.33
 5944.73   25.83 6115.68   23.55 6163.55   25.79 6439.17   27.55 6598.96    23.7
#Mann= 3 ,-1 , 0
 2456.58     .15       0 4911.36    .015       0 5040.52     .15       0
#XS Ineff= 3 ,-1
 2410.97 4285.69   22.13 4354.32 4849.19   21.28 5104.59 5262.83   22.48
Permanent Ineff=
       F       F       F
#Block Obstruct= 2 ,-1
 2444.12 2514.25   20.39 3150.64 3262.84   20.51
Bank Sta=4911.36,5040.52
XS Rating Curve= 0
Exp/Cntr=0.3,0.1

Type RM Length L Ch R = 1 ,8821.352,248.12,243.89,241.18
BEGIN DESCRIPTION:
added high contraction expansion to remove dip in profile due to transition from concrete to earthen section.
only about a 0.2 increase at this section and upstream section  for the 100-yr
END DESCRIPTION:
XS GIS Cut Line= 4
     3207314.886    13806740.644     3204882.847    13807526.356
     3204807.435    13807555.856      3203283.17    13808180.583
#Sta/Elev= 30
 2403.83      24 3186.38   22.19 3284.92   23.32  3517.7   21.48 3560.62   22.88
 3720.36   20.83 3931.37    22.3 4272.97   20.39 4420.35   22.17 4648.99   19.98
 4897.08   20.41 4959.51      18 4976.36    13.3 4990.02   12.61  4990.7    8.58
 4999.34    8.12 5009.53    8.55 5010.04   12.55 5025.12    13.7 5040.49   19.16
 5062.59   20.94 5141.41   21.18 5194.37   19.06 5468.88    23.2 6035.71      25
 6101.11   23.51 6251.82   25.58 6322.07   23.83 6584.98   26.62 6687.94   24.42
#Mann= 4 ,-1 , 0
 2403.83     .07       0  3517.7     .15       0 4959.51    .015       0
 5040.49     .15       0
#XS Ineff= 3 ,-1
 3296.45 3560.81   22.84 3658.95 4420.13   22.37 5142.41  5295.8   21.19
Permanent Ineff=
       F       F       F
#Block Obstruct= 1 ,-1
 2449.12 3281.72   23.27
Bank Sta=4897.08,5062.59
XS Rating Curve= 0
Exp/Cntr=0.8,0.6

Type RM Length L Ch R = 1 ,8577.462,745.07,778.78,784.9
XS GIS Cut Line= 4
     3207218.986    13806516.878     3204823.955    13807284.494
     3204716.518    13807332.186     3203207.327    13807975.807
#Sta/Elev= 30
 2425.35   22.39 2925.29   21.91 3181.78   23.28 3408.21   21.96 4047.35   22.59
 4196.67   19.79 4395.07   21.12 4654.31   19.41 4903.86   22.56  4923.2    22.1
 4941.23   16.91 4952.09   16.47  4973.7   12.21 4986.88    7.27 5007.17    6.79
 5025.86       8 5058.77   18.98 5108.87   20.91 5245.72    20.3 5435.12   22.19
 5657.14   20.46 5741.03   23.04 5904.78   24.43 6009.57   22.51 6095.81   24.49
 6221.57   23.44 6286.79   26.15 6455.15   24.76 6545.38    26.3 6698.64    24.1
#Mann= 6 ,-1 , 0
 2425.35     .07       0 3408.21     .15       0 4903.86     .07       0
  4923.2    .032       0 5108.87     .07       0 5245.72     .15       0
#XS Ineff= 4 ,-1
 2375.32 3702.73   23.11  3716.7 4900.89   22.55 5433.78 5758.37   22.18
 5901.28 6274.31   24.39
Permanent Ineff=
       F       F       F       F
#Block Obstruct= 1 ,-1
 2339.33 3182.46   23.23
Bank Sta=4923.2,5108.87
XS Rating Curve= 0
Exp/Cntr=0.3,0.1

Type RM Length L Ch R = 1 ,7798.68 ,208.42,201.08,180.67
XS GIS Cut Line= 5
     3207187.019    13806341.062     3205505.374    13806337.595
     3204589.997    13806570.494     3204477.583    13806593.368
      3202264.17    13807140.225
#Sta/Elev= 30
 2316.34   23.16  3220.1   22.51 3323.93   22.34  3397.2   20.56 3456.24   22.34
 3691.28   22.33  4116.3   21.39 4272.03    19.8 4325.27   21.64  4518.8   21.82
 4616.34   19.65 4667.25    21.5 4910.38   22.38 4971.16    8.18 4995.86    7.74
 5003.41    5.58 5006.78     6.4 5009.08    8.56 5038.45   15.97 5057.36   22.97
 5443.77   20.52  5664.5   23.14 5947.29   24.34 6358.55   23.25 6439.91   24.89
 6672.99   24.34 6743.66   26.14 7165.21   26.25 7268.59   25.08 7337.21   26.38
#Mann= 4 ,-1 , 0
 2316.34     .07       0  3220.1     .15       0 4910.38    .032       0
 5057.36     .07       0
#XS Ineff= 3 ,-1
 2269.78 2947.69   23.59 2994.44  4907.4   22.62 5057.08 5746.74   22.99
Permanent Ineff=
       F       F       F
#Block Obstruct= 1 ,-1
 6016.19 6510.12   23.86
Bank Sta=4910.38,5057.36
XS Rating Curve= 0
Exp/Cntr=0.3,0.1

Type RM Length L Ch R = 1 ,7597.597,934.75,957.61,912.11
XS GIS Cut Line= 6
     3207171.036    13806213.195     3205497.789     13806117.65
     3204555.162    13806365.104     3204427.301    13806413.768
     3204011.264     13806557.54     3202855.552    13806532.861
#Sta/Elev= 30
 2280.04   22.38 2804.95   22.24 2885.77   23.48 3156.74   22.48 3339.15   20.41
  3376.7   22.35 3488.56   22.94 4084.74    21.9 4288.25   20.11 4467.38   21.48
 4629.49   19.61 4769.75   22.44  4931.6   21.95 4973.23    8.13 5000.34    4.07
 5014.45     5.4  5019.1    8.26  5068.4   21.41 5084.47   24.55 5101.15   22.36
 5289.79   23.67 5645.16   21.87 5743.51   24.56 5812.74   23.25 5911.94   24.89
  5985.9    23.2 6158.75   24.71 6225.19   22.82 6307.86   24.64 6663.54   24.48
#Mann= 5 ,-1 , 0
 2280.04     .07       0 3156.74     .15       0  4931.6    .032       0
  5068.4     .12       0 6225.19     .07       0
#XS Ineff= 4 ,-1
 2247.72 4809.65   22.61 5076.92 5735.33   24.48 5740.26 5908.04   24.55
 5910.43 6675.01   24.86
Permanent Ineff=
       F       F       F       F
#Block Obstruct= 2 , 0
         4913.57    20.1
Bank Sta=4931.6,5068.4
XS Rating Curve= 0
Exp/Cntr=0.3,0.1

Type RM Length L Ch R = 1 ,6639.987,873.76,981.93,1021.77
XS GIS Cut Line= 5
     3206979.237    13805493.948     3204944.135    13805419.893
     3203949.063    13805741.949     3203820.106    13805798.682
     3202727.685    13806357.045
#Sta/Elev= 30
 1847.13    21.7 2161.29   21.61 2264.45   23.29  2788.8   21.14  2982.9   22.34
 3111.05    20.7 3141.07   22.26 3159.12   18.98 3181.63   18.62 3276.16   18.77
 3306.18   21.67 3360.15   20.89 4259.07   22.69 4873.18   21.94 4929.56   20.55
 5024.31    3.67 5070.44   19.18 5109.06   18.85 5191.63   21.01 5575.44   24.23
 5629.69   21.72 5686.85   22.04 5737.39    25.3 5828.35   22.42 5922.69   22.63
 5990.08   24.82 6023.77   16.19 6040.61   22.46 6065.16   23.67  6297.2   23.09
#Mann= 7 ,-1 , 0
 1847.13     .07       0 3360.15     .15       0 4873.18     .07       0
 4929.56    .032       0 5070.44     .07       0 5109.06     .12       0
 5629.69     .07       0
#XS Ineff= 1 ,-1
 1729.04 4548.88   22.78
Permanent Ineff=
       F
#Block Obstruct= 3 ,-1
 2970.12 3440.47    21.9 3300.48 3422.28    18.7 5573.38  6297.2   24.16
Bank Sta=4929.56,5070.44
XS Rating Curve= 0
Exp/Cntr=0.3,0.1

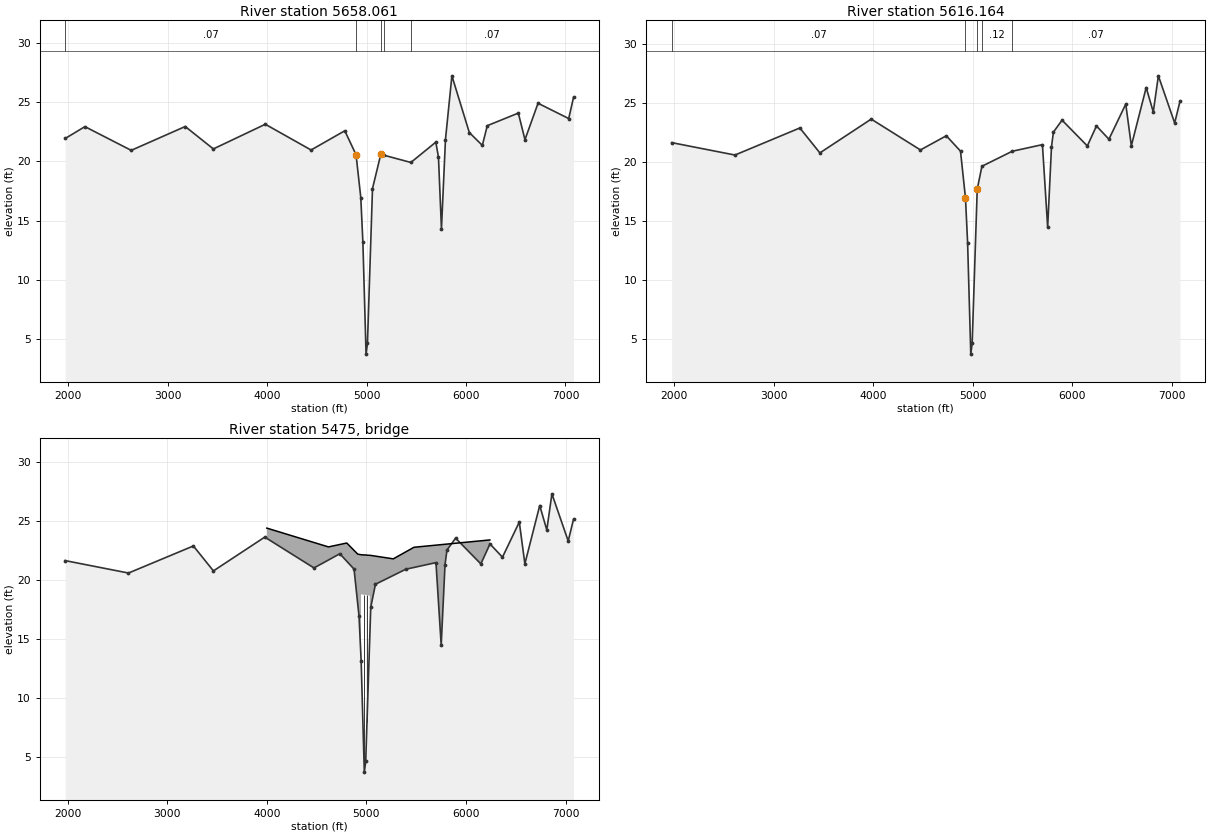
Type RM Length L Ch R = 1 ,5658.061,40.2,41.9,44.1
XS GIS Cut Line= 4
     3206855.724    13805010.275     3203900.066    13804841.838
      3203783.49    13804834.277     3201747.636    13804840.304
#Sta/Elev= 30
 1967.91   21.93 2166.12   22.93 2631.94   20.93 3175.15   22.94 3458.17   21.05
 3980.74   23.13 4440.95   20.96 4780.17   22.58 4893.47   20.56 4941.12   16.95
 4962.33   13.17 4994.19    3.76 5008.11    4.66 5058.88   17.71 5142.66   20.61
 5178.48   20.51 5444.84   19.91 5695.68   21.62 5722.52   20.36 5752.52   14.31
 5792.85   21.84 5857.52   27.21 6032.81   22.43 6163.74   21.35 6213.58   23.01
 6525.77   24.07 6592.52   21.83 6724.03    24.9 7032.53   23.61 7081.05   25.39
#Mann= 5 ,-1 , 0
 1967.91     .07       0 4893.47    .032       0 5142.66     .07       0
 5178.48     .12       0 5444.84     .07       0
#Block Obstruct= 2 , 0
                         5554.31           21.17
Bank Sta=4893.47,5142.66
XS Rating Curve= 0
Exp/Cntr=0.5,0.3

Type RM Length L Ch R = 1 ,5616.164,290.06,282.03,283.93
XS GIS Cut Line= 4
     3206846.778    13804965.546     3203902.478     13804801.91
     3203784.972    13804794.289     3201747.636    13804750.845
#Sta/Elev= 30
 1975.65   21.65 2611.16    20.6 3262.74   22.89 3463.93   20.78 3979.36   23.64
  4473.7   21.03 4733.36   22.23 4876.01   20.93 4926.12   16.95 4947.33   13.17
 4979.19    3.76 4993.11    4.66 5043.88   17.71 5091.07   19.65 5395.59   20.92
 5698.64   21.48 5751.22   14.49 5789.63    21.3 5809.02   22.54 5895.79   23.55
 6149.47   21.37 6241.19   23.06 6366.36   21.94  6535.5   24.91 6591.41   21.38
 6740.59   26.31 6811.65   24.24 6862.93    27.3 7026.51   23.31 7080.04   25.15
#Mann= 5 ,-1 , 0
 1975.65     .07       0 4926.12    .032       0 5043.88     .07       0
 5091.07     .12       0 5395.59     .07       0
#Block Obstruct= 2 , 0
                         5558.62           21.37
Bank Sta=4926.12,5043.88
XS Rating Curve= 0
Exp/Cntr=0.5,0.3

Type RM Length L Ch R = 3 ,5475    ,,,
Node Photo=G:\C2001-041 Harris County FEMA\1-Armand Bayou\Willow Springs Bayou\Survey info\Fairmont PKWY - 3225\MVC-008S.JPG
BEGIN DESCRIPTION:
Fairmont Parkway (modeled as single bridge)
END DESCRIPTION:
Bridge Culvert--1,0,-1,-1, 0
Deck Dist Width WeirC Skew NumUp NumDn MinLoCord MaxHiCord MaxSubmerge Is_Ogee
63,148,2.6,0, 15, 15, , , 0.95, 0, 0,0,,
    4000    4619    4803 4913.17 4945.87 4945.88 4977.51 4996.86 5006.12 5034.45
 5034.46 5067.81    5270    5478    6240
    24.4   22.81   23.14    22.2   22.15   22.15   22.13   22.13   22.11    22.1
    22.1   22.06    21.8   22.78    23.4
       0       0       0       0       0    18.8   18.75   18.75   18.75   18.67
       0       0       0       0       0
    4000    4619    4803 4913.17 4945.87 4945.88 4977.51 4996.86 5006.12 5034.45
 5034.46 5067.81    5270    5478    6240
    24.4   22.81   23.14    22.2   22.15   22.15   22.13   22.13   22.11    22.1
    22.1   22.06    21.8   22.78    23.4
       0       0       0       0       0    18.8   18.75   18.75   18.75   18.67
       0       0       0       0       0
Pier Skew, UpSta & Num, DnSta & Num=  ,4977.507, 4 ,4977.507, 4 , 3 , 3 , 0 ,,
     1.4     1.4     2.5     2.5
       0   16.75  16.751    18.8
     1.4     1.4     2.5     2.5
       0   16.75  16.751    18.8
Pier Skew, UpSta & Num, DnSta & Num=  ,5006.119, 4 ,5006.119, 4 , 3 , 3 , 0 ,,
     1.4     1.4     2.5     2.5
       0   16.75   16.75    18.8
     1.4     1.4     2.5     2.5
       0   16.75   16.75    18.8
BR Coef=-1 , 1 , 0 ,1.25, 0 ,,,0.8,0,2,0,
WSPro=,,,, 1 ,,,, 0 ,,,, 0 ,,,,-1 ,-1 ,-1 , 0 , 0 , 0 , 0 , 0
BC Design=,, 0 ,, 0 ,,,,,,
BC HTab HWMax=27.3