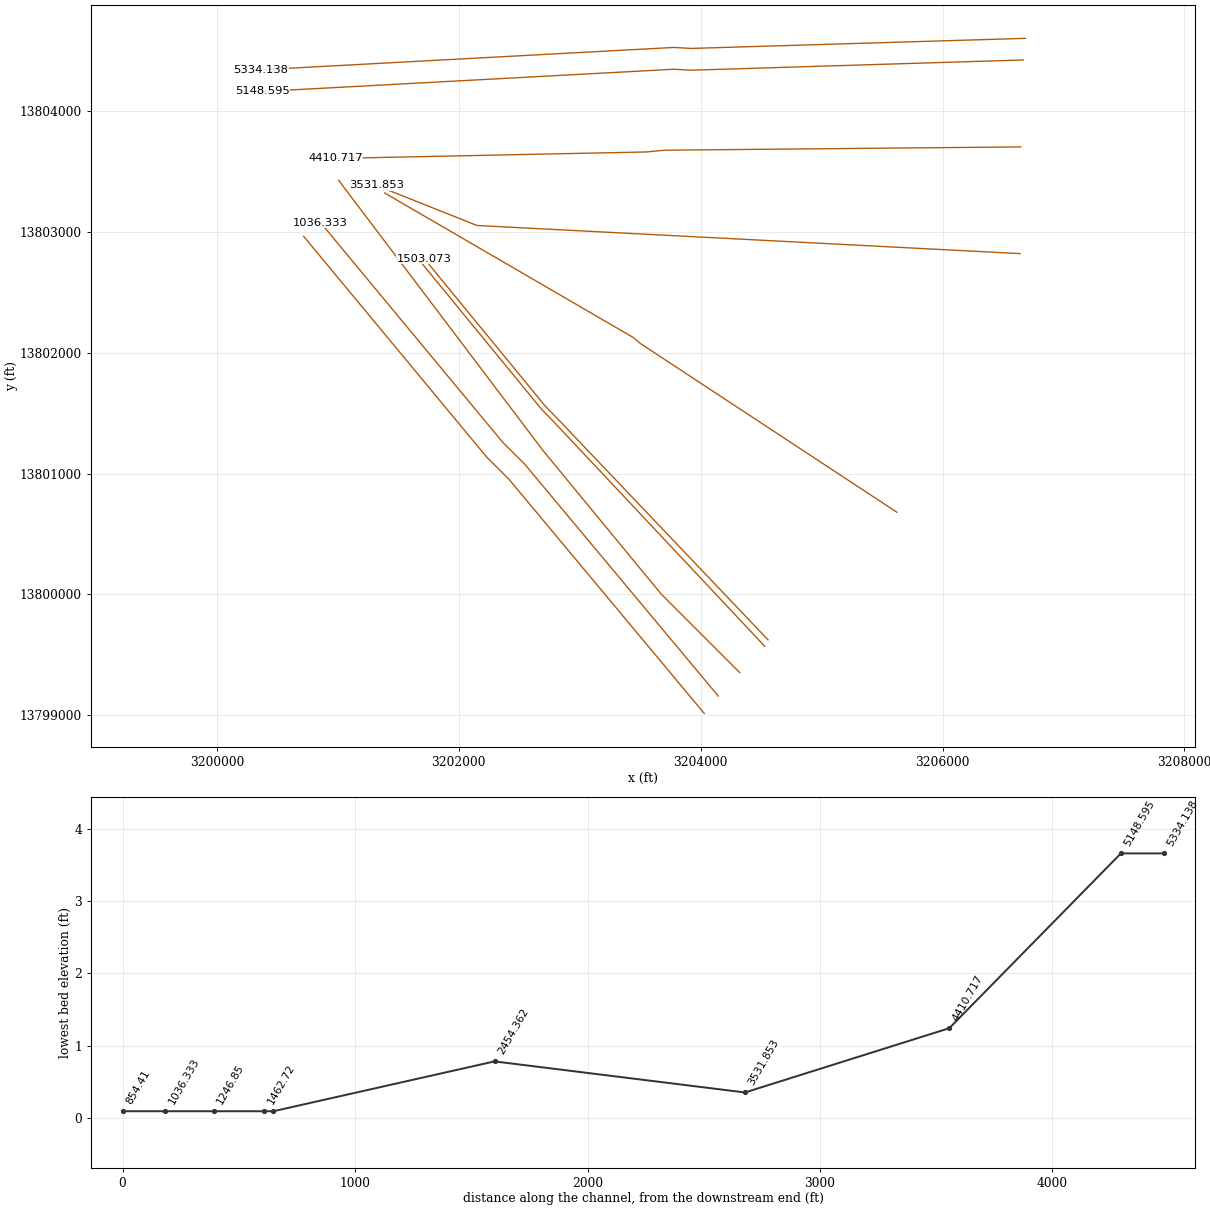
HEC-RAS study B112-00-00.prj: B112-00-00

--- B112-00-00.g02 (geometry) --- (continued)

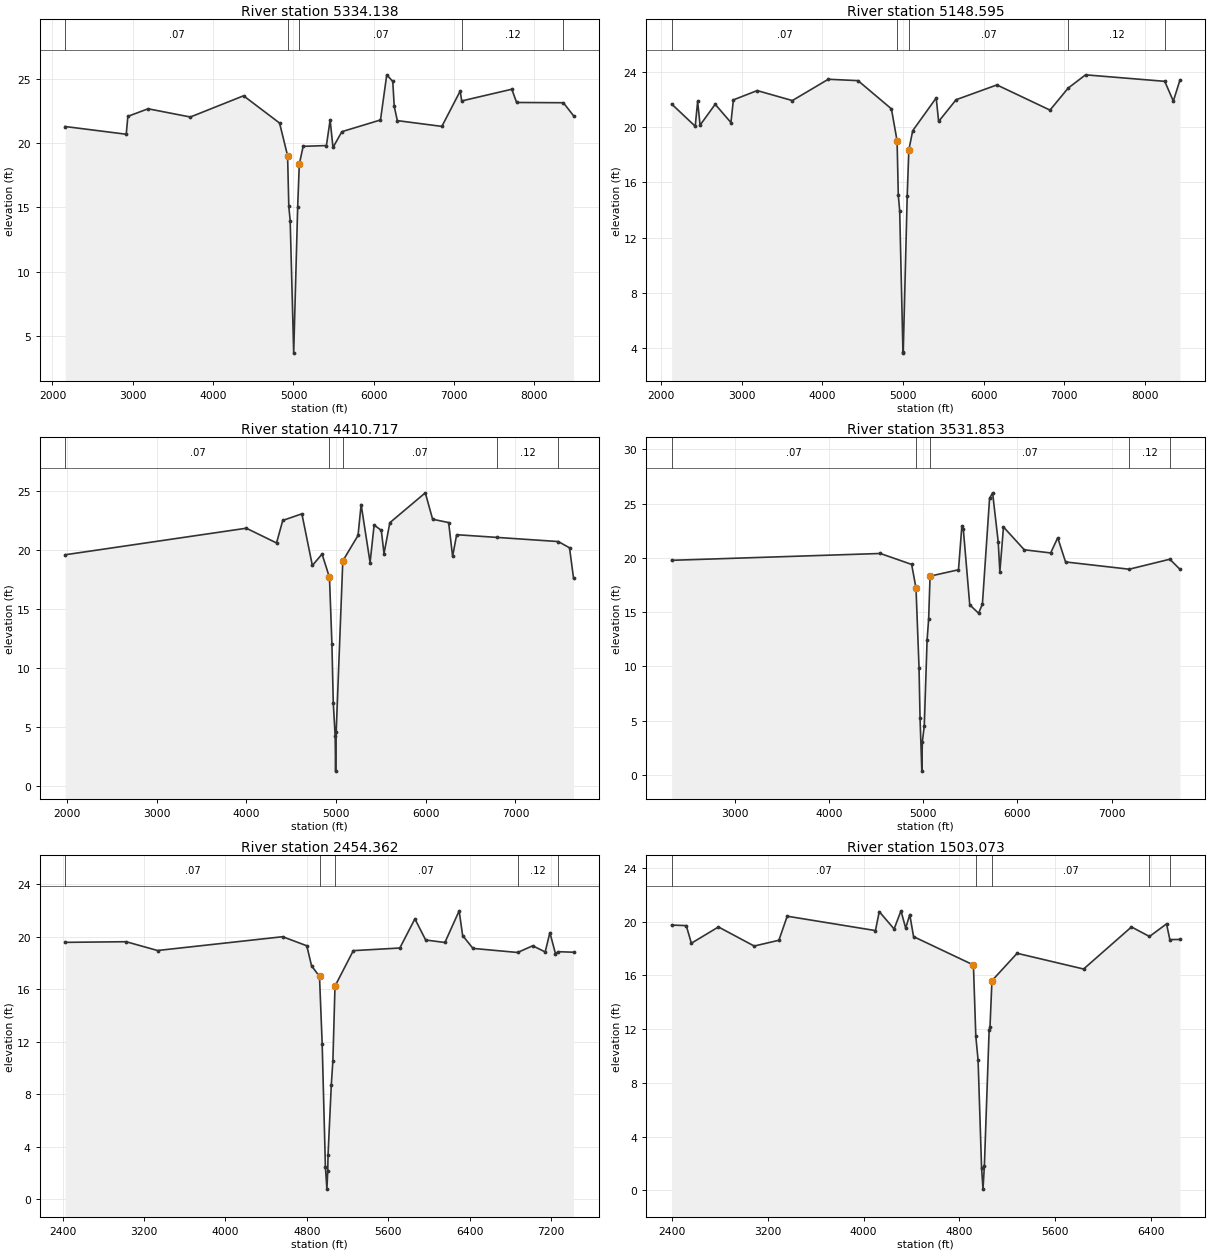
Type RM Length L Ch R = 1 ,5334.138,188.35,185.54,190.18
XS GIS Cut Line= 4
     3206685.753    13804598.765     3203921.983    13804515.334
     3203775.983    13804523.399     3200364.174    13804338.873
#Sta/Elev= 30
 2158.71   21.28 2918.65   20.68 2938.65   22.07 3190.21   22.66 3716.91   22.02
 4379.21   23.67 4827.28   21.55 4927.15   19.01 4942.29   15.07 4959.46   13.95
 5003.16    3.66 5052.77   15.05 5072.85   18.35 5120.81   19.74 5410.29    19.8
 5456.82   21.79 5492.22   19.65 5602.89   20.88 6083.62   21.79 6161.54    25.3
 6236.49   24.79 6254.61   22.86 6293.14   21.74 6847.66   21.29 7076.11   24.04
 7094.59   23.27 7718.44   24.18 7778.25   23.15 8360.19   23.13 8486.76   22.12
#Mann= 5 ,-1 , 0
 2158.71     .07       0 4927.15    .032       0 5072.85     .07       0
 7094.59     .12       0 8360.19     .07       0
Bank Sta=4927.15,5072.85
XS Rating Curve= 0
Exp/Cntr=0.5,0.3

Type RM Length L Ch R = 1 ,5148.595,693.95,737.88,687.22
XS GIS Cut Line= 4
     3206667.861    13804419.848     3203919.487    13804335.198
     3203775.879     13804343.13     3200373.895    13804159.136
#Sta/Elev= 30
 2133.29   21.67 2425.13   20.06 2455.15   21.86 2485.16   20.14 2672.43   21.65
 2867.81   20.33  2898.3   21.97 3193.33   22.64 3629.11   21.92  4074.4   23.46
 4442.74   23.36 4856.95   21.32 4927.15   19.01 4942.29   15.07 4959.46   13.95
 4999.82    3.73 5003.16    3.66 5052.77   15.05 5072.85   18.35 5120.81   19.74
 5412.08   22.11 5442.12   20.41 5658.58   21.98 6164.33   23.05 6822.42   21.23
 7047.65   22.82 7262.92   23.78 8244.74   23.31 8351.04   21.88 8433.75   23.41
#Mann= 5 ,-1 , 0
 2133.29     .07       0 4927.15    .032       0 5072.85     .07       0
 7047.65     .12       0 8244.74     .07       0
Bank Sta=4927.15,5072.85
XS Rating Curve= 0
Exp/Cntr=0.3,0.1

Type RM Length L Ch R = 1 ,4410.717,881.75,878.86,697.61
XS GIS Cut Line= 4
     3206645.417    13803700.924     3203700.443    13803673.762
     3203552.612    13803659.295     3200977.933    13803605.786
#Sta/Elev= 30
  1978.5   19.58 3998.43   21.83 4335.25   20.58 4404.71   22.49 4617.87   23.05
 4734.67   18.67 4842.88   19.64 4925.73   17.66 4952.88   12.02 4967.98    7.03
 4988.87    4.24 4994.19    1.24 5000.34    4.52 5074.27   19.06 5244.18   21.22
 5278.64   23.84 5378.55   18.92 5423.54    22.1 5503.68   21.65 5533.69   19.68
 5598.96    22.3 5994.28   24.83 6075.95   22.59 6254.52   22.31 6298.86   19.44
 6343.87   21.28 6797.04   21.05  7477.3    20.7 7602.63   20.17 7647.37    17.6
#Mann= 5 ,-1 , 0
  1978.5     .07       0 4925.73    .032       0 5074.27     .07       0
 6797.04     .12       0  7477.3     .07       0
#Block Obstruct= 2 , 0
                          7235.5           21.55
Bank Sta=4925.73,5074.27
XS Rating Curve= 0
Exp/Cntr=0.3,0.1

Type RM Length L Ch R = 1 ,3531.853,1140.98,1077.49,930.77
XS GIS Cut Line= 3
     3206641.024    13802818.538       3202150.2    13803051.131
     3201318.235    13803382.128
#Sta/Elev= 30
 2333.55   19.78 4547.09   20.41 4879.31    19.4 4925.44   17.21 4957.54    9.87
 4968.12    5.28  4987.2     .35 4992.33    3.03 5013.31    4.53 5042.78    12.4
 5059.46   14.37 5074.56   18.32 5376.07   18.91 5411.74   22.92 5427.02   22.67
 5495.42   15.68 5589.52    14.9 5629.77   15.75 5705.74   25.49 5737.84      26
 5797.42   21.49  5814.8   18.73 5853.35   22.85 6074.01   20.75  6353.8   20.46
  6428.9   21.86 6511.66   19.63 7186.56   18.96 7617.94   19.88 7725.78   18.95
#Mann= 5 ,-1 , 0
 2333.55     .07       0 4925.44    .032       0 5074.56     .07       0
 7186.56     .12       0 7617.94     .07       0
#Block Obstruct= 2 , 0
                          5412.8           22.89
Bank Sta=4925.44,5074.56
XS Rating Curve= 0
Exp/Cntr=0.3,0.1

Type RM Length L Ch R = 1 ,2454.362,963.84,951.29,858.53
XS GIS Cut Line= 4
     3205621.195    13800680.477     3203501.993    13802074.666
     3203443.314    13802124.146     3201385.666    13803320.373
#Sta/Elev= 30
 2425.83   19.56 3024.04   19.61 3332.77   18.94 4561.71   19.99 4799.06    19.3
 4845.91   17.77  4923.9   16.97  4950.2   11.83 4981.88    2.48 4996.58     .78
 5004.85    2.15 5007.84    3.38 5039.94    8.74 5055.47   10.55  5076.1   16.23
 5256.11   18.93 5712.99   19.13 5861.06   21.35 5966.89   19.74 6155.87   19.55
 6295.76   21.96 6329.99   20.08 6431.36    19.1 6870.08   18.79 7018.23    19.3
 7140.89   18.83 7187.04    20.3 7241.64   18.71 7269.57   18.85 7419.37   18.81
#Mann= 5 ,-1 , 0
 2425.83     .07       0  4923.9    .032       0  5076.1     .07       0
 6870.08     .12       0 7269.57     .07       0
Bank Sta=4923.9,5076.1
XS Rating Curve= 0
Exp/Cntr=0.3,0.1

Type RM Length L Ch R = 1 ,1503.073,41.81,40.35,40.11
XS GIS Cut Line= 4
     3204556.637    13799624.865     3202809.179    13801460.267
     3202715.932     13801555.52     3201715.595    13802774.917
#Sta/Elev= 30
 2397.98   19.74 2519.81    19.7 2562.45   18.39 2788.62    19.6 3087.05   18.18
 3293.28   18.61 3362.79    20.4 4099.63   19.33 4131.35   20.74 4255.48   19.45
 4312.67    20.8 4352.14   19.51 4386.09   20.52 4417.92   18.88 4917.72   16.77
 4937.65   11.47 4956.62     9.7 4985.78    1.67 4997.71     .09 5009.27    1.83
 5048.82    11.9 5056.26   12.18 5072.35    15.6  5282.6   17.64 5837.81   16.47
 6237.48    19.6 6388.03   18.89 6530.32   19.83 6557.82   18.66 6642.72   18.67
#Mann= 5 ,-1 , 0
 2397.98     .07       0 4937.65    .032       0 5072.35     .07       0
 6388.03     .12       0 6557.82     .07       0
Bank Sta=4917.72,5072.35
XS Rating Curve= 0
Exp/Cntr=0.5,0.3

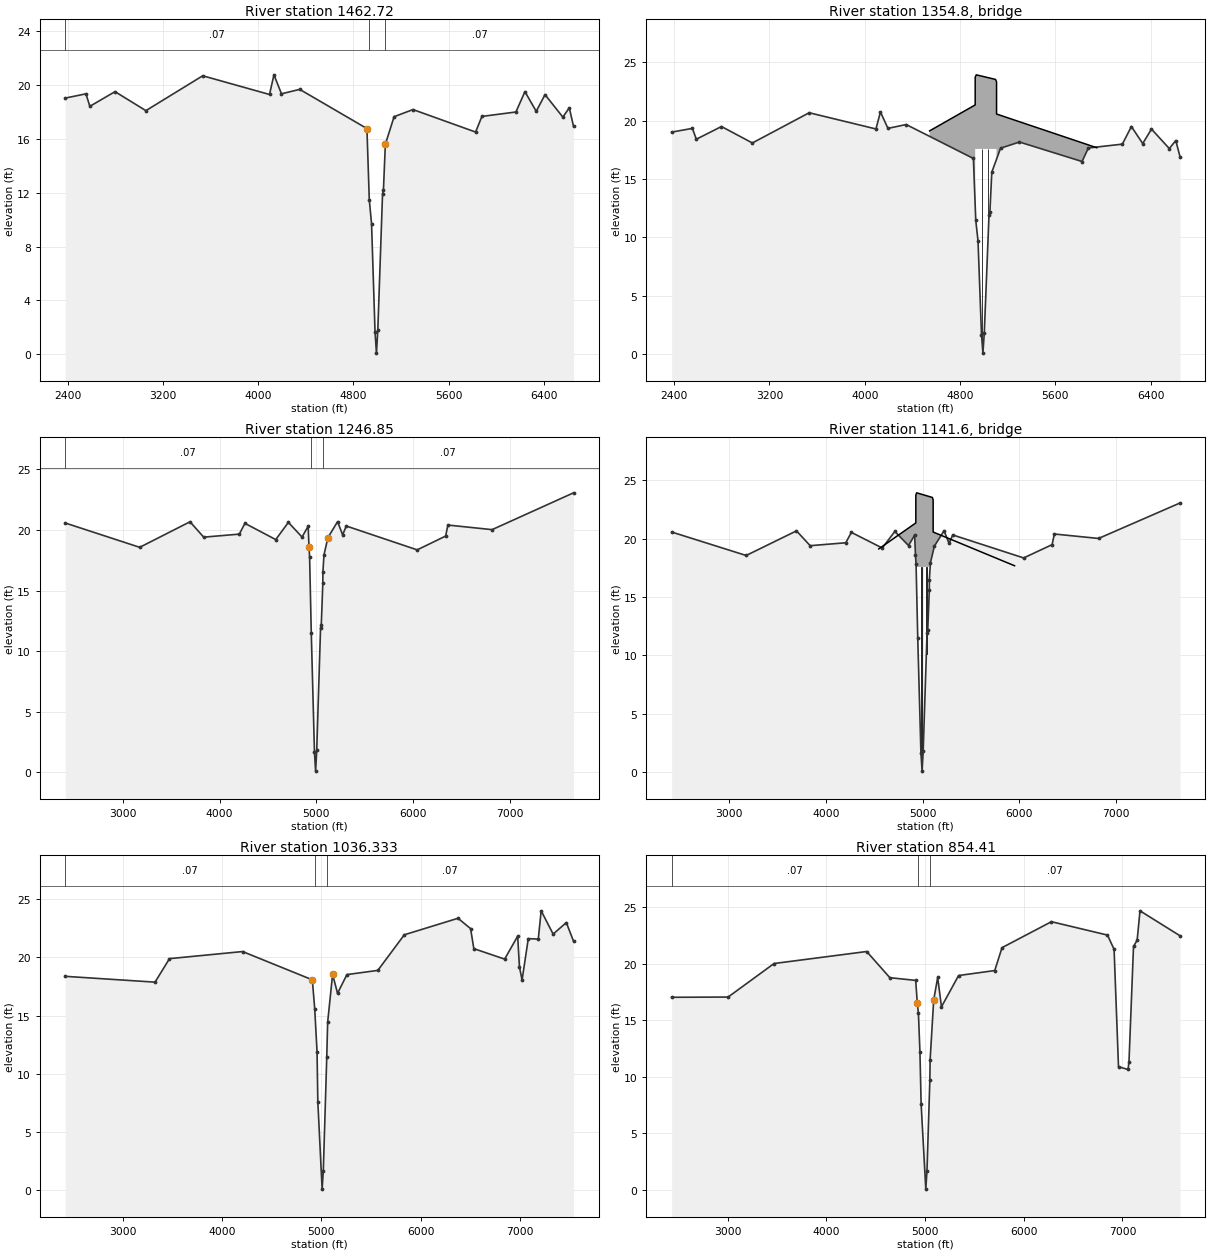
Type RM Length L Ch R = 1 ,1462.72 ,237.71,215.87,197.41
XS GIS Cut Line= 4
       3204529.8     13799571.19      3202780.35    13801432.536
      3202686.12    13801528.793      3201684.67    13802749.548
#Sta/Elev= 30
 2379.38   19.03 2553.46   19.35 2586.26   18.42 2797.54   19.51 3056.94    18.1
  3534.1   20.69 4094.71    19.3 4132.15   20.76 4195.27   19.35 4348.59   19.68
 4912.72   16.77 4932.65   11.47 4951.62     9.7 4980.78    1.67 4992.71     .09
 5004.27    1.83 5043.82    11.9 5051.26   12.18 5067.35    15.6 5140.84   17.65
 5299.59   18.18 5825.28   16.51 5878.12   17.67  6163.7      18 6239.39   19.51
 6334.43   18.05 6408.11   19.29 6557.74   17.62 6612.02   18.31  6647.5   16.93
#Mann= 3 ,-1 , 0
 2379.38     .07       0 4932.65    .032       0 5067.35     .07       0
Bank Sta=4912.72,5067.35
XS Rating Curve= 0
Exp/Cntr=0.5,0.3

Type RM Length L Ch R = 3 ,1354.8  ,,,
Node Photo=G:\C2001-041 Harris County FEMA\1-Armand Bayou\Willow Springs Bayou\Survey info\Fairmont PKWY - 3225\MVC-008S.JPG
BEGIN DESCRIPTION:
Red Bluff (north)
END DESCRIPTION:
Bridge Culvert--1,0,-1,-1, 0
Deck Dist Width WeirC Skew NumUp NumDn MinLoCord MaxHiCord MaxSubmerge Is_Ogee
67,41,2.6,0, 8, 8, , , 0.95, 0, 0,0,,
    4545 4927.874927.887  4936.85098.7595107.227 5107.23    5949
  19.136   21.36 23.7325 23.9397  23.545 23.3398   20.58   17.69
       0       0   17.59   17.59   17.59   17.59       0       0
    4545 4927.874927.887  4936.85098.7595107.227 5107.23    5949
  19.136   21.36 23.7325 23.9397  23.545 23.3398   20.58   17.69
       0       0   17.59   17.59   17.59   17.59       0       0
Pier Skew, UpSta & Num, DnSta & Num=  ,4987, 4 ,4987, 4 , 3 , 3 , 0 ,,
    1.35    1.35     2.8     2.8
       0   15.21  15.211  17.711
    1.35    1.35     2.8     2.8
       0   15.21  15.211  17.711
Pier Skew, UpSta & Num, DnSta & Num=  ,5037, 4 ,5037, 4 , 3 , 3 , 0 ,,
    1.35    1.35     2.8     2.8
       0   15.21   15.21   17.71
    1.35    1.35     2.8     2.8
       0   15.21   15.21   17.71
BR Coef=-1 , 1 , 0 ,1.25, 0 ,,,0.8,0,2,0,
WSPro=,,,, 1 ,,,, 0 ,,,, 0 ,,,,-1 ,-1 ,-1 , 0 , 0 , 0 , 0 , 0
BC Design=,, 0 ,, 0 ,,,,,,
BC HTab HWMax=20.76

Type RM Length L Ch R = 1 ,1246.85 ,195.69,210.52,233.23
XS GIS Cut Line= 4
     3204322.309    13799354.141     3203672.889     13800003.56
     3202698.761    13801186.431     3201005.632    13803424.608
#Sta/Elev= 30
 2402.94   20.58  3173.4   18.57 3693.75   20.68 3835.25   19.41  4203.6   19.66
 4261.46   20.55 4580.44   19.21    4711   20.63 4852.34   19.42 4915.55   20.31
 4924.33   18.61 4930.52    17.8    4948   11.47 4980.78    1.67 4992.71     .09
 5004.27    1.83 5043.82    11.9 5051.26   12.18 5067.35    15.6    5068   16.51
 5078.86   17.93 5119.84   19.37  5219.9   20.69 5272.21    19.6 5309.85   20.33
 6043.17   18.36 6337.62    19.5 6360.69   20.41  6817.8   20.03 7660.15   23.07
#Mann= 3 ,-1 , 0
 2402.94     .07       0    4948    .032       0 5067.35     .07       0
Bank Sta=4924.33,5119.84
XS Rating Curve= 0
Exp/Cntr=0.5,0.3

Type RM Length L Ch R = 3 ,1141.6  ,,,
BEGIN DESCRIPTION:
Red Bluff (south)
END DESCRIPTION:
Bridge Culvert--1,0,-1,-1, 0
Deck Dist Width WeirC Skew NumUp NumDn MinLoCord MaxHiCord MaxSubmerge Is_Ogee
100,41,2.6,0, 8, 8, , , 0.95, 0, 0,0,,
    4545 4927.874927.887  4936.85098.7595107.227 5107.23    5949
  19.136   21.36 23.7325 23.9397  23.545 23.3398   20.58   17.69
       0       0   17.59   17.59   17.59   17.59       0       0
    4545 4927.874927.887  4936.85098.7595107.227 5107.23    5949
  19.136   21.36 23.7325 23.9397  23.545 23.3398   20.58   17.69
       0       0   17.59   17.59   17.59   17.59       0       0
Pier Skew, UpSta & Num, DnSta & Num=  ,4987, 4 ,4987, 4 , 3 , 3 , 0 ,,
    1.35    1.35     2.8     2.8
       0   15.21  15.211  17.711
    1.35    1.35     2.8     2.8
       0   15.21  15.211  17.711
Pier Skew, UpSta & Num, DnSta & Num=  ,5037, 4 ,5037, 4 , 3 , 3 , 0 ,,
    1.35    1.35     2.8     2.8
       0   15.21   15.21   17.71
    1.35    1.35     2.8     2.8
       0   15.21   15.21   17.71
BR Coef=-1 , 1 , 0 ,1.25, 0 ,,,0.8,0,2,0,
WSPro=,,,, 1 ,,,, 0 ,,,, 0 ,,,,-1 ,-1 ,-1 , 0 , 0 , 0 , 0 , 0
BC Design=,, 0 ,, 0 ,,,,,,
BC HTab HWMax=23.07

Type RM Length L Ch R = 1 ,1036.333,187.44,181.92,182.22
XS GIS Cut Line= 4
     3204145.128     13799159.68     3202544.162    13801077.675
     3202364.668    13801255.608     3200855.613    13803075.734
#Sta/Elev= 30
 2421.82   18.38 3326.04   17.88 3471.26    19.9 4206.99   20.51 4908.57   18.08
 4932.65    15.6 4956.18    11.9    4964    7.61 5007.29     .09 5019.22    1.67
    5054   11.47    5063   14.44 5112.77   18.55 5162.34   16.92 5256.76   18.53
 5567.55   18.89 5834.38   21.95 6374.65   23.37 6501.36   22.48 6533.88   20.76
 6843.87   19.86 6975.17   21.83 6992.97   19.19 7019.38   18.06 7081.86   21.62
 7182.57   21.58 7211.47   24.01 7332.15   22.01 7464.74      23 7537.26    21.4
#Mann= 3 ,-1 , 0
 2421.82     .07       0 4932.65    .032       0    5054     .07       0
#Block Obstruct= 2 , 0
         4206.92   20.51 6382.25           23.36
Bank Sta=4908.57,5112.77
XS Rating Curve= 0
Exp/Cntr=0.5,0.3

Type RM Length L Ch R = 1 ,854.41  ,757.76,854.41,976.02
XS GIS Cut Line= 4
     3204028.831    13799016.546     3202411.426    13800955.803
     3202231.707    13801133.959     3200717.045    13802960.848
#Sta/Elev= 30
 2432.03   17.02 3003.95   17.04  3469.7      20 4408.42   21.06 4642.91   18.75
 4905.04   18.51    4921   16.51 4932.65    15.6    4948   12.18    4960    7.61
 5007.29     .09 5019.22    1.67 5048.38     9.7    5051   11.47 5087.28   16.77
  5127.8   18.77 5166.12   16.18 5339.56   18.94 5705.96   19.38 5779.84    21.4
 6280.59   23.69 6848.59   22.51 6915.53   21.25 6960.23   10.89 7056.94   10.65
 7066.39   11.31 7112.38   21.51 7149.03   22.05 7178.14   24.65 7583.43   22.45
#Mann= 3 ,-1 , 0
 2432.03     .07       0 4932.65    .032       0    5051     .07       0
#Block Obstruct= 2 , 0
         4409.56   21.05 6327.65           23.77
Bank Sta=4921,5087.28
XS Rating Curve= 0
Exp/Cntr=0.3,0.1

Chan Stop Cuts=-1